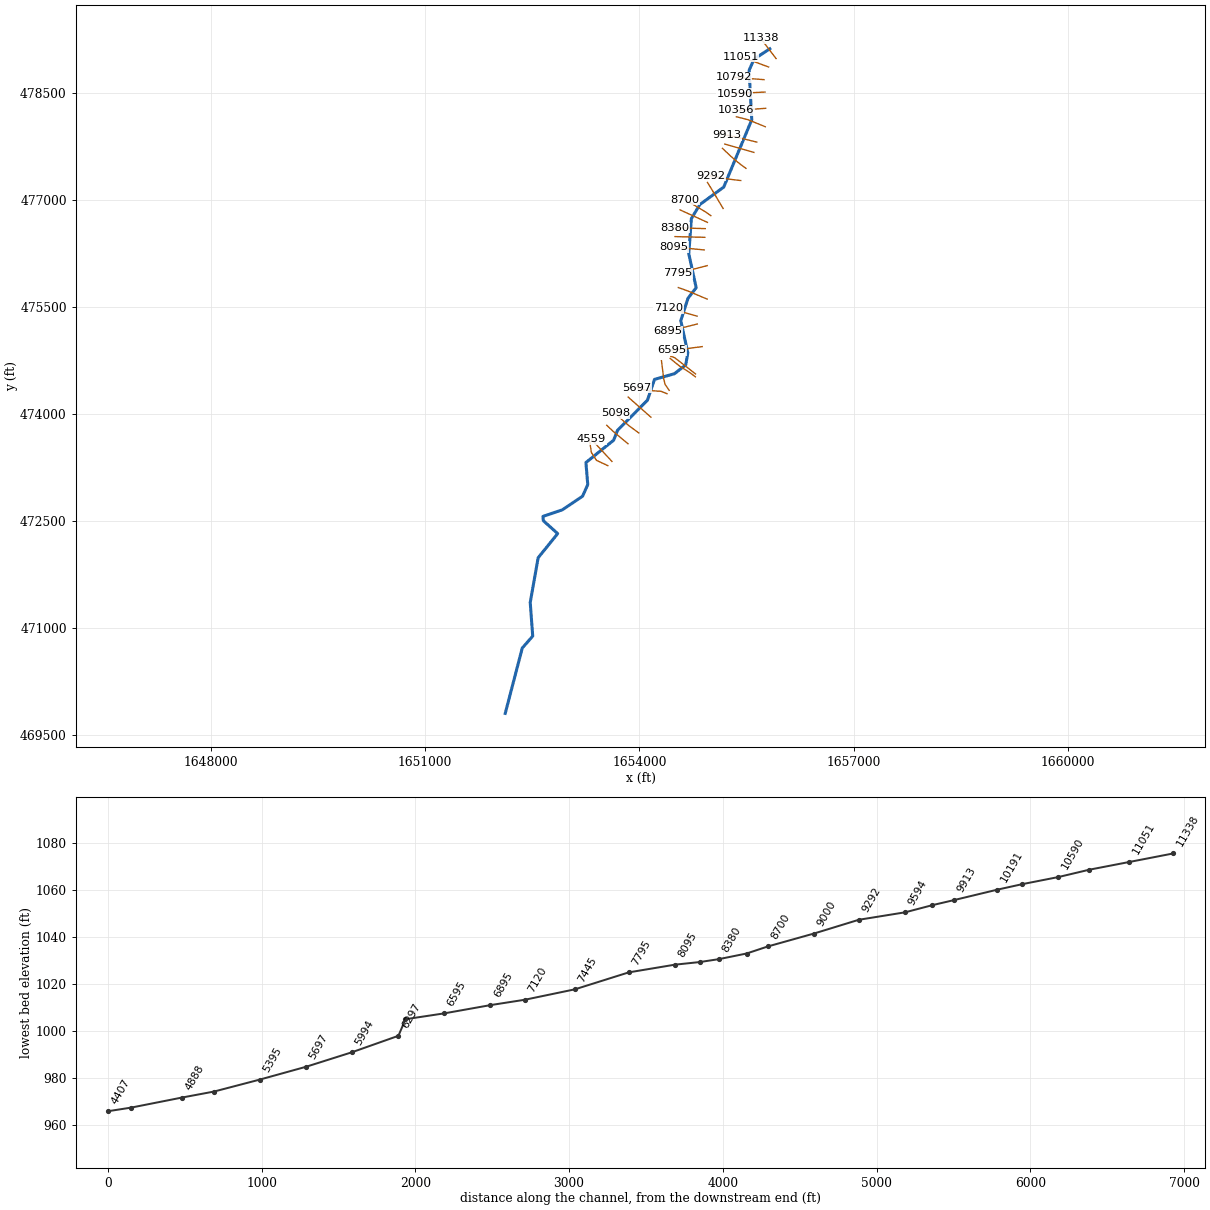
--- LftFkMagtyRn.prj (project) ---

Proj Title=LftFkMagtyRn
Current Plan=p01
Default Exp/Contr=0,0
English Units
Geom File=g01
Flow File=f01
Plan File=p01
BEGIN DESCRIPTION:
---------- MODELED AS PART OF WVEM CTP PROGRAM, 2025----------
Stream Name: Left Fork Maggoty Run
Flood Zone: AFH
Marshall County, WV
HEC-RAS Version: RAS 6.6
Vertical Datum: NAVD88
Projection: NAD 1983 StatePlane West Virginia N FIPS 4701 (US Feet)
Terrain: 1-meter West Virginia FEMA R3 South Central (collected 2018-2019)
Land Use: 2024 NLCD
Hydrologic Method:
Duda et al., "Estimation of magnitude and frequency of floods for rural, unregulated streams in and near Virginia and West Virginia." September 8, 2025.
Additional Model Notes:
KWSE modeled as Normal Depth
END DESCRIPTION:
DSS Export Rating Curves= 0
DSS Export Rating Curve Sorted= 0
DSS Export Volume Flow Curves= 0
DXF OffsetX= 0
DXF OffsetY= 0
DXF ScaleX= 0
DXF ScaleY= 0

--- LftFkMagtyRn.p01 (plan) ---

Plan Title=Floodplain
Program Version=6.60
Short Identifier=Floodplain
Geom File=g01
Flow File=f01
Subcritical Flow
K Sum by GR= 0
Std Step Tol= 0.01
Critical Tol= 0.01
Num of Std Step Trials= 20
Max Error Tol= 0.3
Flow Tol Ratio= 0.001
Split Flow NTrial= 30
Split Flow Tol= 0.02
Split Flow Ratio= 0.02
Log Output Level= 0
Friction Slope Method= 1
Unsteady Friction Slope Method= 2
Unsteady Bridges Friction Slope Method= 1
Parabolic Critical Depth
Global Vel Dist= 0 , 0 , 0
Global Log Level= 0
CheckData=False
Encroach Param=-1 ,0,0, 0
Flow Ratio Tolerance=0.1
Flow Ratio Min Ratio=0.5
Flow Ratio Max Ratio=4
Flow Ratio Max Iterations= 10
Mapping Interval=1HOUR
Computation Time Step Use Courant=        0
Computation Time Step Use Time Series=    0
Computation Time Step Count To Double=0
Computation Time Step Max Doubling=0
Computation Time Step Max Halving=0
Computation Time Step Residence Courant=0
Run HTab= 0
Run UNet= 0
Run Sediment= 0
Run PostProcess= 0
Run WQNet= 0
Run RASMapper=-1
UNET Theta= 0
UNET Theta Warmup= 0
UNET ZTol= 0
UNET ZSATol= 0
UNET MxIter= 0
UNET Max Iter WO Improvement= 0
UNET MaxInSteps= 0
UNET DtIC= 0
UNET DtMin= 0
UNET MaxCRTS= 0
UNET WFStab= 0
UNET SFStab= 0
UNET WFX= 1
UNET SFX= 1
UNET Gravity=32.17405
UNET 1D Methodology=Finite Difference
UNET DSS MLevel= 1
UNET Pardiso=0
UNET DZMax Abort= 0
UNET Use Existing IB Tables= 0
UNET Froude Reduction=False
UNET Froude Limit= 0
UNET Froude Power= 0
UNET D1 Cores= 0
UNET WindReference=Eulerian
UNET WindDragFormulation=Hsu (1988)
UNET D2 Coriolis=0
UNET D2 Cores= 0
UNET D2 Theta= 1
UNET D2 Theta Warmup= 1
UNET D2 Z Tol= 0.01
UNET D2 Volume Tol= 0.01
UNET D2 Max Iterations= 20
UNET D2 Advanced Convergence=0
UNET D2 WS Max Tol=0.15
UNET D2 WS RMS Tol=0.002
UNET D2 WS Stall Tol=1
UNET D2 Equation= 0
UNET D2 RampUpFraction=0.1
UNET D2 TimeSlices= 1
UNET D2 Turbulence Formulation=Non-Conservative (original)
UNET D2 Eddy Viscosity=0.3
UNET D2 Transverse Eddy Viscosity=0.1
UNET D2 Smagorinsky Mixing=0
UNET D2 BCVolumeCheck=0
UNET D2 Cores=0
UNET D2 SolverType=PARDISO (Direct)
UNET D2 Minimum Iterations= 3
UNET D2 Maximum Iterations= 30
UNET D2 Restart Number= 10
UNET D2 Relaxation Coeff=1.3
UNET D2 SOR Precondition Iterations= 10
UNET D2 ILUT Maximum Fill= 8
UNET D2 ILUT Tolerance=1E-08
UNET D2 Convergence Tolerance=0.00001
PS Theta= 1
PS WS Tol= 0.01
PS Volume Tol= 0.01
PS Max Iterations= 20
PS Equation= 0
PS Advance Time Step=-1
PS Target Courant=0.9
PS Time Slices= 1
PS Iterate With 2D=0
PS Project Initial WSE from DS=-1
PS Ramp Up Initial WSE from US=-1
PS Cores=0
UNET D1D2 MaxIter= 0
UNET D1D2 ZTol=0.01
UNET D1D2 QTol=0.1
UNET D1D2 MinQTol=1
Write IC File= 0
Write IC File at Fixed DateTime=0
Write IC File at Sim End=0
Echo Input=False
Echo Parameters=False
Echo Output=False
Write Detailed= 0
HDF Write Warmup=0
HDF Write Time Slices=0
HDF Flush=0
HDF Compression= 1
HDF Chunk Size= 1
HDF Spatial Parts= 1
HDF Use Max Rows=0
HDF Fixed Rows= 1
Calibration Method= 0
Calibration Iterations= 20
Calibration Max Change=0.05
Calibration Tolerance=0.2
Calibration Maximum=1.5
Calibration Minimum=0.5
Calibration Optimization Method= 1
WQ AD Non Conservative
WQ ULTIMATE=-1
WQ Max Comp Step=1HOUR
WQ Output Interval=15MIN
WQ Output Selected Increments= 0
WQ Create Restart=0
WQ Fixed Restart=0
WQ System Summary=0
WQ Write To DSS=0
Sorting and Armoring Iterations= 10
XS Update Threshold= 0.02
Bed Roughness Predictor= 0
Processes Affected by Predictor=Sediment Only
Hydraulics Update Threshold= 0.02
Energy Slope Method= 1
Volume Change Method= 1
Sediment Retention Method= 0
Sediment TS Multiplier= 1
Warm Up Method= 0
XS Weighting Method= 0
Number of US Weighted Cross Sections= 1
Number of DS Weighted Cross Sections= 1
Upstream XS Weight=0
Main XS Weight=1
Downstream XS Weight=0
Number of DS XS's Weighted with US Boundary= 1
Upstream Boundary Weight= 1
Weight of XSs Associated with US Boundary= 0
Number of US XS's Weighted with DS Boundary= 1
Downstream Boundary Weight= 0.5
Weight of XSs Associated with DS Boundary= 0.5
Percentile Method= 0
Sediment Output Level= 3
Mass or Volume Output= 0
Output Increment Type= 1
Profile and TS Output Increment= 1
Transport Output Increment 1
XS Output Flag= 0
XS Output Increment= 10
Read HDF5 Sediment Hotstart= 0
Sediment Hotstart Type= 0
Write Gradation File= 0
Read Gradation Hotstart= 0
Write HDF5 File= 1
Write Binary Output= 1
Write DSS Sediment File= 0
DSS Sediment Output Type= 1
SV Curve= 0
Specific Gage Flag= 0
Subcell Erosion Methods= 0
Subcell Deposition Methods= 0
Advection Scheme= 1
Matrix Solver= 0
Implicit Weighting Factor= 1
Maximum Outer Loop Convergence Iterations= 5
Convergence Maximum Absolute= 0.001
Convergence RMSE= 0.0001
Grain Fractions Max Abs Error= 0.001
Max Subgrid Regions= 1
Max Subgrid Length Scale= 3.402823E+38
Initial Layer Thickness= 3
Min Layer Thickness= 0.1
Max Layer Thickness= 6
Number of Layers= 5

--- LftFkMagtyRn.f01 (steady flow) ---

Flow Title=Flow
Program Version=6.60
Number of Profiles= 1
Profile Names=P100yr
River Rch & RM=LftFkMagtyRn,Main,11338
    1070
River Rch & RM=LftFkMagtyRn,Main,5098
    1280
Boundary for River Rch & Prof#=LftFkMagtyRn,Main            , 1
Up Type= 0
Dn Type= 3
Dn Slope=0.037
DSS Import GetInterval= 0
DSS Import GetPeak= 0
DSS Import FillOption= 0

--- LftFkMagtyRn.g01 (geometry) ---

Geom Title=Geometry
Program Version=6.60

River Reach=LftFkMagtyRn    ,Main
Reach XY= 30
       1655826.4        479115.2       1655604.8        478970.4
       1655537.2        478812.8     1655574.219      478121.094
1655181.65590004477177.719099956      1654846.68      476932.617
1654728.18730356476734.033036655     1654692.383      476242.188
     1654795.837      475767.517     1654681.641      475620.117
     1654580.078      475306.641     1654678.711      474854.492
      1654649.35      474685.689     1654492.188        474562.5
     1654211.914      474482.422     1654113.281      474191.406
      1653693.75      473768.125        1653640.      473630.625
     1653251.875        473317.5       1653277.6         473008.
       1653205.2         472846.       1652923.2        472655.6
       1652649.6        472562.4        1652656.        472501.6
       1652856.4        472321.6       1652582.8        471983.2
        1652472.         471356.       1652506.8        470885.2
       1652360.4         470718.     1652122.082      469802.506

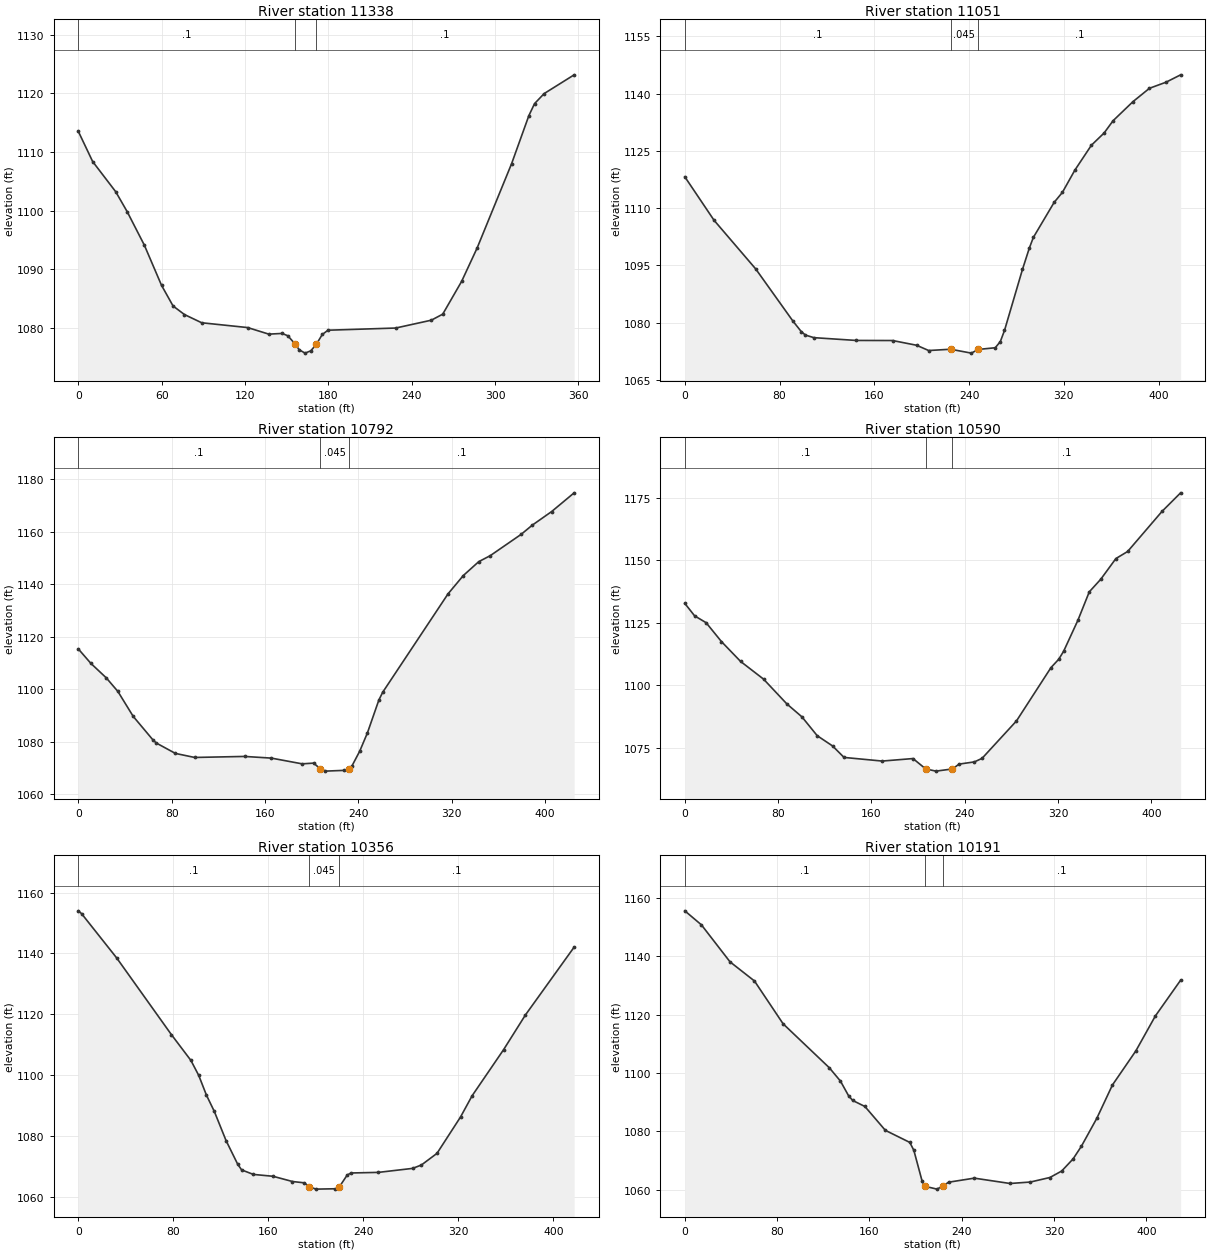
Type RM Length L Ch R = 1 ,11338   ,279,287.3,292.4
XS GIS Cut Line= 2
1655914.84406211 478978.596649851655698.00352616479262.011034561
#Sta/Elev= 30
       0 1113.52    10.3 1108.38    26.9 1103.23    35.1 1099.85    47.5 1094.12
    59.9 1087.25    68.2 1083.73    76.4 1082.27    88.8 1080.87   121.9 1080.05
   137.1 1078.93   146.7 1079.05   150.8 1078.65  156.311077.172     159 1076.26
   163.2 1075.69   167.3 1076.08  171.261077.171   175.6 1078.87   179.7  1079.6
   228.4 1079.97   254.1 1081.31   262.3 1082.34   275.9 1087.93   287.1 1093.65
   311.9 1108.03   324.3 1116.21   328.4 1118.26   335.3 1119.97   356.9 1123.17
#Mann= 3 ,-1,0
       0      .1       0  156.31    .045       0  171.26      .1       0
Bank Sta=156.31,171.26
XS Rating Curve= 0 ,0
Exp/Cntr(USF)=0,0
Exp/Cntr=0.3,0.1

Type RM Length L Ch R = 1 ,11051   ,256.7,259.5,263
XS GIS Cut Line= 2
1655809.91059491 478860.257089011655417.41065484 479005.89121327
#Sta/Elev= 30
       0 1118.21    24.7 1106.82    59.9 1094.07    91.4 1080.38    98.4 1077.65
   101.9 1076.76     109 1076.09   144.7 1075.36   175.4 1075.34   195.7  1074.1
   205.9 1072.72   224.4 1073.06   241.9 1072.04   247.71073.001   262.1 1073.45
   266.4 1075.07   269.9 1077.97   285.1 1093.98   290.9 1099.57   294.3 1102.35
   311.8  1111.5   318.8 1114.13   329.3 1119.94   343.3 1126.48     354 1129.67
   361.6 1132.89   378.3 1137.86   392.3 1141.38   406.3 1142.97   418.6  1144.9
#Mann= 3 ,-1,0
       0      .1       0   224.4    .045       0   247.7      .1       0
Bank Sta=224.4,247.7
XS Rating Curve= 0 ,0
Exp/Cntr(USF)=0,0
Exp/Cntr=0.3,0.1

Type RM Length L Ch R = 1 ,10792   ,200.6,201.2,203.7
XS GIS Cut Line= 6
1655744.88358809478683.0636009281655657.63441876478689.738784418
1655582.84487018478695.4605577591655483.13936092478703.130161837
1655408.36588842478708.8506228331655321.12492117478715.525150165
#Sta/Elev= 30
       0 1115.33    10.8  1109.8      24 1104.29    33.9 1099.13      47 1089.65
    63.8 1080.74    66.8 1079.48    83.2 1075.51    99.7 1073.97   142.5 1074.36
   165.5 1073.72   191.8 1071.54   201.7 1071.81  207.191069.728   211.6 1068.76
     228 1069.05  232.111069.729   234.6 1070.79   241.2 1076.37   247.8 1083.34
   257.6 1095.86   260.9 1098.83   316.9 1136.33     330 1143.31   343.2 1148.59
     353 1150.86   379.4 1158.95   389.2 1162.54   405.7 1167.69     425 1174.83
#Mann= 3 ,-1,0
       0      .1       0  207.19    .045       0  232.11      .1       0
Bank Sta=207.19,232.11
XS Rating Curve= 0 ,0
Exp/Cntr(USF)=0,0
Exp/Cntr=0.3,0.1

Type RM Length L Ch R = 1 ,10590   ,233.5,233.9,234.1
XS GIS Cut Line= 6
1655758.88959282478509.1816168761655671.48884899478505.014630456
1655596.57397257478501.4427872041655496.68736132478496.680657629
 1655421.7724849478493.1091424561655334.37174108478488.942156036
#Sta/Elev= 30
       0 1132.76     8.4 1127.78    18.3 1125.02    31.4 1117.48    47.8 1109.54
    67.5 1102.45    87.5 1092.52   100.4 1087.35   113.5 1079.81   126.7 1075.69
   136.5 1071.11   169.2 1069.66   195.6 1070.66  206.521066.504   215.3 1065.63
  229.441066.503   235.1 1068.44   248.2 1069.32   254.8 1070.74   284.3 1085.72
   313.9 1107.08   320.5 1110.39   324.7 1113.58   336.9 1125.94   346.7 1137.37
   356.6 1142.45   369.5 1150.69   379.6 1153.53   409.1 1169.59     425    1177
#Mann= 3 ,-1,0
       0      .1       0  206.52    .045       0  229.44      .1       0
Bank Sta=206.52,229.44
XS Rating Curve= 0 ,0
Exp/Cntr(USF)=0,0
Exp/Cntr=0.3,0.1

Type RM Length L Ch R = 1 ,10356   ,167.5,165.3,159.9
XS GIS Cut Line= 2
1655769.54008158478281.5398825691655353.11106877 478251.01219178
#Sta/Elev= 30
       0 1153.99     2.7 1153.08    32.3 1138.52    78.3 1113.38    94.8 1104.87
   101.4 1099.94   107.9 1093.45   114.5 1088.14   124.4 1078.55   134.2 1070.79
   137.5 1068.93   147.4 1067.45   163.9 1066.84   180.3 1065.12   190.2 1064.69
   194.5 1063.42     200 1062.62   216.5 1062.74   219.91063.432   226.4 1067.25
   229.6 1067.92   252.7 1068.12   281.5 1069.43   288.9 1070.55     302 1074.36
   321.8 1086.29   331.6 1093.29   358.1 1108.42   376.5 1119.82   417.5 1142.08
#Mann= 3 ,-1,0
       0      .1       0   194.5    .045       0   219.9      .1       0
Bank Sta=194.5,219.9
XS Rating Curve= 0 ,0
Exp/Cntr(USF)=0,0
Exp/Cntr=0.3,0.1

Type RM Length L Ch R = 1 ,10191   ,276,278.3,279.2
XS GIS Cut Line= 6
1655763.78217234478023.2014035881655682.77085142 478056.26793851
1655613.33234201 478084.610729591655520.45719968 478121.68841134
  1655446.974407478141.2316793351655358.55824526478163.234260008
#Sta/Elev= 30
       0 1155.51    14.4 1150.71    39.2 1138.04    60.4 1131.48    85.2 1116.83
   125.2  1101.8   134.9 1097.22   141.9 1092.22   145.5 1090.59   156.1 1088.52
   173.8 1080.36     195 1076.22   198.5 1073.51   205.6 1063.08  207.951061.226
   218.5 1060.23  223.491061.229   228.6  1062.6   250.9 1063.99   281.9 1062.16
   299.5 1062.66   316.4 1064.21   326.6 1066.42   336.5 1070.57   343.6 1074.84
   357.1  1084.5   370.6 1095.88   390.9 1107.56   407.8 1119.51   429.7 1131.76
#Mann= 3 ,-1,0
       0      .1       0  207.95    .045       0  223.49      .1       0
Bank Sta=207.95,223.49
XS Rating Curve= 0 ,0
Exp/Cntr(USF)=0,0
Exp/Cntr=0.3,0.1

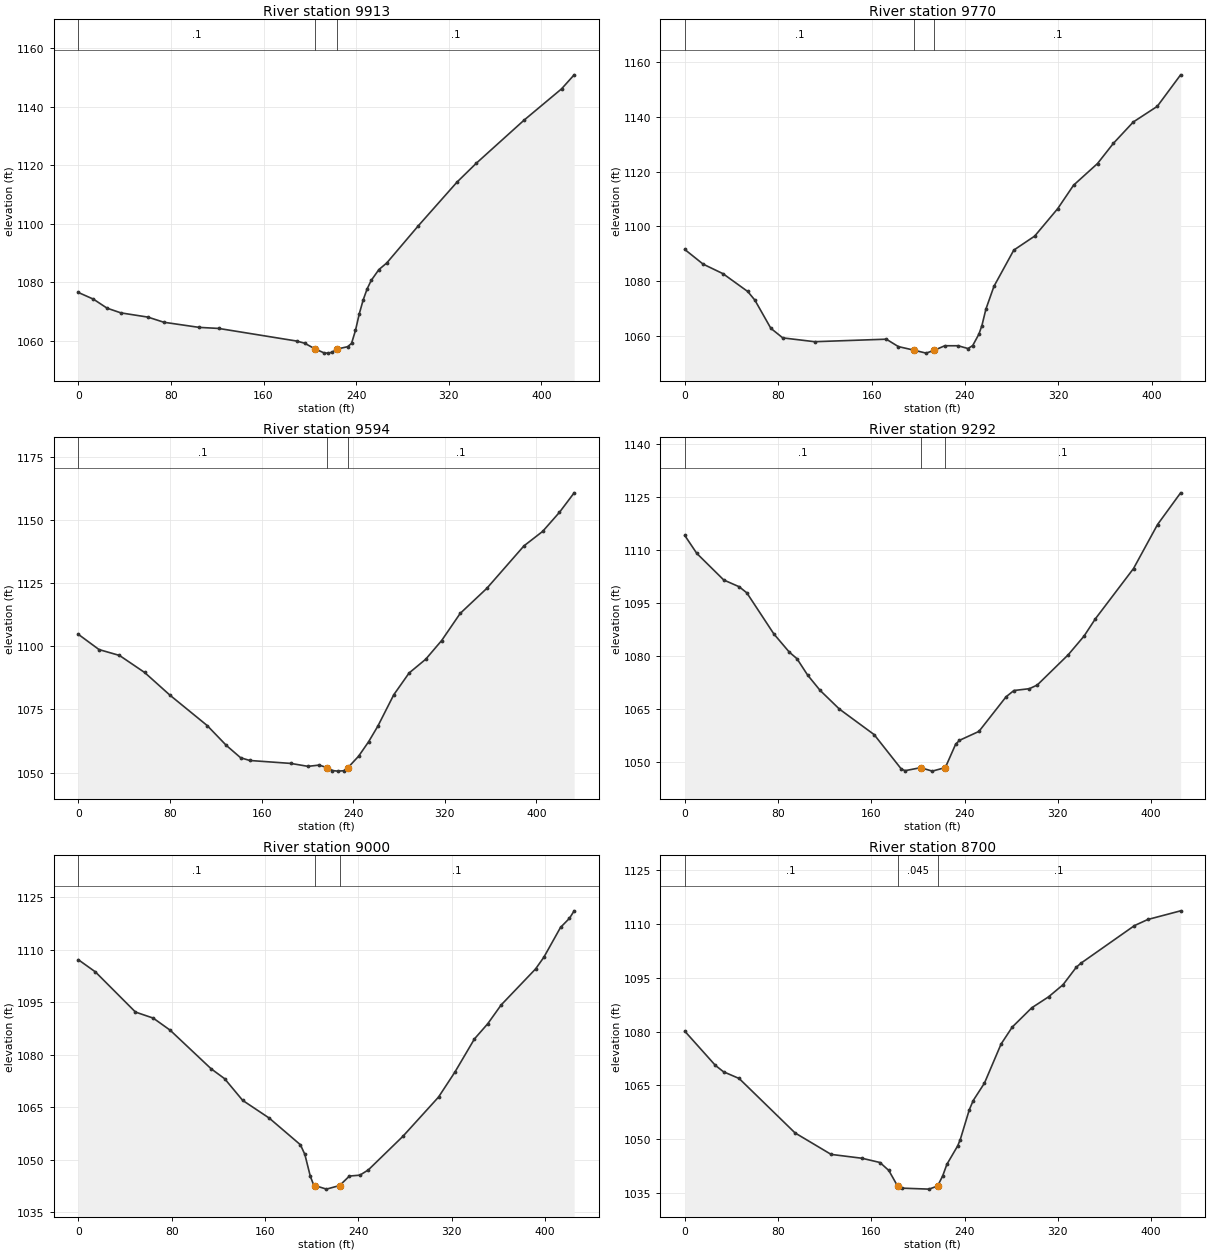
Type RM Length L Ch R = 1 ,9913    ,142.5,142.4,141.9
XS GIS Cut Line= 3
1655645.14727794477808.2003647161655328.23572877477885.169386695
1655227.97779776477904.841076002
#Sta/Elev= 30
       0 1076.57    13.1 1074.27    24.8 1071.21    36.8 1069.59    60.1 1068.15
    73.9 1066.39   104.3 1064.64   121.2 1064.28   188.7 1059.96   195.5 1059.22
  204.541057.276   212.3 1055.91   215.7 1055.84   219.1 1056.13  223.871057.274
   232.6 1058.03     236 1059.17   239.4  1063.6   242.7 1069.31   246.1 1074.07
   249.5 1077.82     253 1080.69   259.6 1084.38   266.4 1086.64   293.7 1099.36
   327.1 1114.28   343.8 1120.74     385 1135.44   417.4 1146.14   428.3 1150.94
#Mann= 3 ,-1,0
       0      .1       0  204.54    .045       0  223.87      .1       0
Bank Sta=204.54,223.87
XS Rating Curve= 0 ,0
Exp/Cntr(USF)=0,0
Exp/Cntr=0.3,0.1

Type RM Length L Ch R = 1 ,9770    ,178.8,176.5,170.9
XS GIS Cut Line= 2
 1655604.8001379477663.6046277211655196.48053218477780.267372211
#Sta/Elev= 30
       0 1091.58    15.7 1086.22    32.7 1082.73    53.9 1076.21      60 1073.07
    73.7 1062.74    83.9 1059.24   111.2 1057.84   172.6 1058.76   182.9 1056.06
  196.541054.713   206.7 1053.66  213.731054.714   222.7 1056.36   234.1 1056.36
   242.6 1055.34   246.6 1056.43   251.9 1060.59   254.5 1063.75   257.9 1069.75
   264.8  1078.1   281.8 1091.35   299.7 1096.48   319.4 1106.51     333  1115.1
   353.5 1123.02   367.1 1130.41   384.2 1138.24   404.7 1143.95   424.7 1155.48
#Mann= 3 ,-1,0
       0      .1       0  196.54    .045       0  213.73      .1       0
Bank Sta=196.54,213.73
XS Rating Curve= 0 ,0
Exp/Cntr(USF)=0,0
Exp/Cntr=0.3,0.1

Type RM Length L Ch R = 1 ,9594    ,298.8,302.4,308.8
XS GIS Cut Line= 6
1655492.69445993477439.8679245861655419.82551117477493.857646003
 1655358.2521435477542.398559421 1655281.5711945477608.603479505
1655227.19597517477660.2595441791655163.75843801477720.524843588
#Sta/Elev= 30
       0 1104.73    18.1 1098.69    35.9 1096.38    57.9 1089.63      80 1080.66
   112.5 1068.65   129.2  1060.8   141.7 1055.91   149.7 1054.83   185.5 1053.67
   200.5 1052.51   210.3 1053.01  217.521051.946   221.9 1050.84   226.6 1050.62
   231.7 1050.77  235.291051.945   244.7 1056.52   253.4 1062.22   261.5 1068.41
   275.4 1080.82   288.8 1089.44   303.3 1094.88   317.2 1102.27   333.4    1113
   356.6 1122.89   389.1 1139.72   405.4 1145.44   420.1    1153   432.9 1160.69
#Mann= 3 ,-1,0
       0      .1       0  217.52    .045       0  235.29      .1       0
Bank Sta=217.52,235.29
XS Rating Curve= 0 ,0
Exp/Cntr(USF)=0,0
Exp/Cntr=0.3,0.1

Type RM Length L Ch R = 1 ,9292    ,299.7,291.3,281.4
XS GIS Cut Line= 6
1655419.53581358477269.4053390031655332.38080418477279.197642252
1655257.95378767477288.9912578461655159.45792167477306.271078929
1655085.58635026477319.230698675 1654999.4024675477334.350419089
#Sta/Elev= 30
       0 1114.11    10.3 1109.04    33.4 1101.52    46.6 1099.61    53.2 1097.88
    76.4 1086.25    89.6 1081.12    96.2 1079.25   105.4 1074.59     116  1070.3
   132.6 1064.99   162.4 1057.77   185.7 1048.03     189 1047.56   202.3 1048.41
   212.3 1047.43  223.481048.436   232.3 1055.03   235.6 1056.14   252.3 1058.67
   275.6 1068.47   282.3 1070.24   295.6 1070.76   302.3 1071.79   328.9 1080.36
   342.4 1085.62   352.2 1090.54   384.9 1104.76   405.5 1117.21   425.3 1126.18
#Mann= 3 ,-1,0
       0      .1       0   202.3    .045       0  223.48      .1       0
Bank Sta=202.3,223.48
XS Rating Curve= 0 ,0
Exp/Cntr(USF)=0,0
Exp/Cntr=0.3,0.1

Type RM Length L Ch R = 1 ,9000    ,286,300,302.1
XS GIS Cut Line= 6
1655173.38079409476877.8729855871655128.50588384476952.989633262
1655090.04172193477017.3753312531655038.75639142477103.222928584
 1655000.2925576477167.6086265891654954.42946035477242.190498427
#Sta/Elev= 30
       0 1107.09    14.6 1103.62      49 1092.14    64.2 1090.42    78.7 1086.97
   113.9 1075.93   125.4 1073.12   140.9 1066.92   163.6 1061.88   190.4 1054.25
   194.2  1051.5   198.9 1045.24   201.8 1042.75  202.821042.609   212.7 1041.58
  224.031042.609   232.4 1045.31   241.4 1045.57   248.6 1047.06   278.3 1056.67
   308.8 1067.86   322.8 1074.97   339.6 1084.47     351  1088.8   362.5 1094.17
     392 1104.45   399.1 1107.79   413.4 1116.31   421.1 1118.93   425.1 1121.05
#Mann= 3 ,-1,0
       0      .1       0  202.82    .045       0  224.03      .1       0
Bank Sta=202.82,224.03
XS Rating Curve= 0 ,0
Exp/Cntr(USF)=0,0
Exp/Cntr=0.3,0.1

Type RM Length L Ch R = 1 ,8700    ,139.2,138.4,139.7
XS GIS Cut Line= 6
1655000.95430167476776.9014027571654929.57813209476827.985946253
1654865.33416609476866.6866562521654779.67587285476918.287274837
1654715.43223493476956.9883129151654640.48126934477002.139141262
#Sta/Elev= 30
       0  1080.1    26.2 1070.58    33.2 1068.79    46.6 1066.92    94.6 1051.74
   125.5 1045.76   152.1 1044.68   167.4  1043.5     175 1041.28   182.51036.948
   186.5 1036.35   209.5 1036.08  216.821036.947   221.2 1039.76   224.8 1042.99
   234.1 1048.16   236.3 1049.91     244 1058.17   247.4 1060.78     257 1065.61
   271.3 1076.53   280.9 1081.26   297.6 1086.62     312 1089.67   324.4 1093.04
   335.8 1097.92   339.7 1099.03   385.7 1109.53   397.2 1111.24   425.3 1113.65
#Mann= 3 ,-1,0
       0      .1       0   182.5    .045       0  216.82      .1       0
Bank Sta=182.5,216.82
XS Rating Curve= 0 ,0
Exp/Cntr(USF)=0,0
Exp/Cntr=0.3,0.1

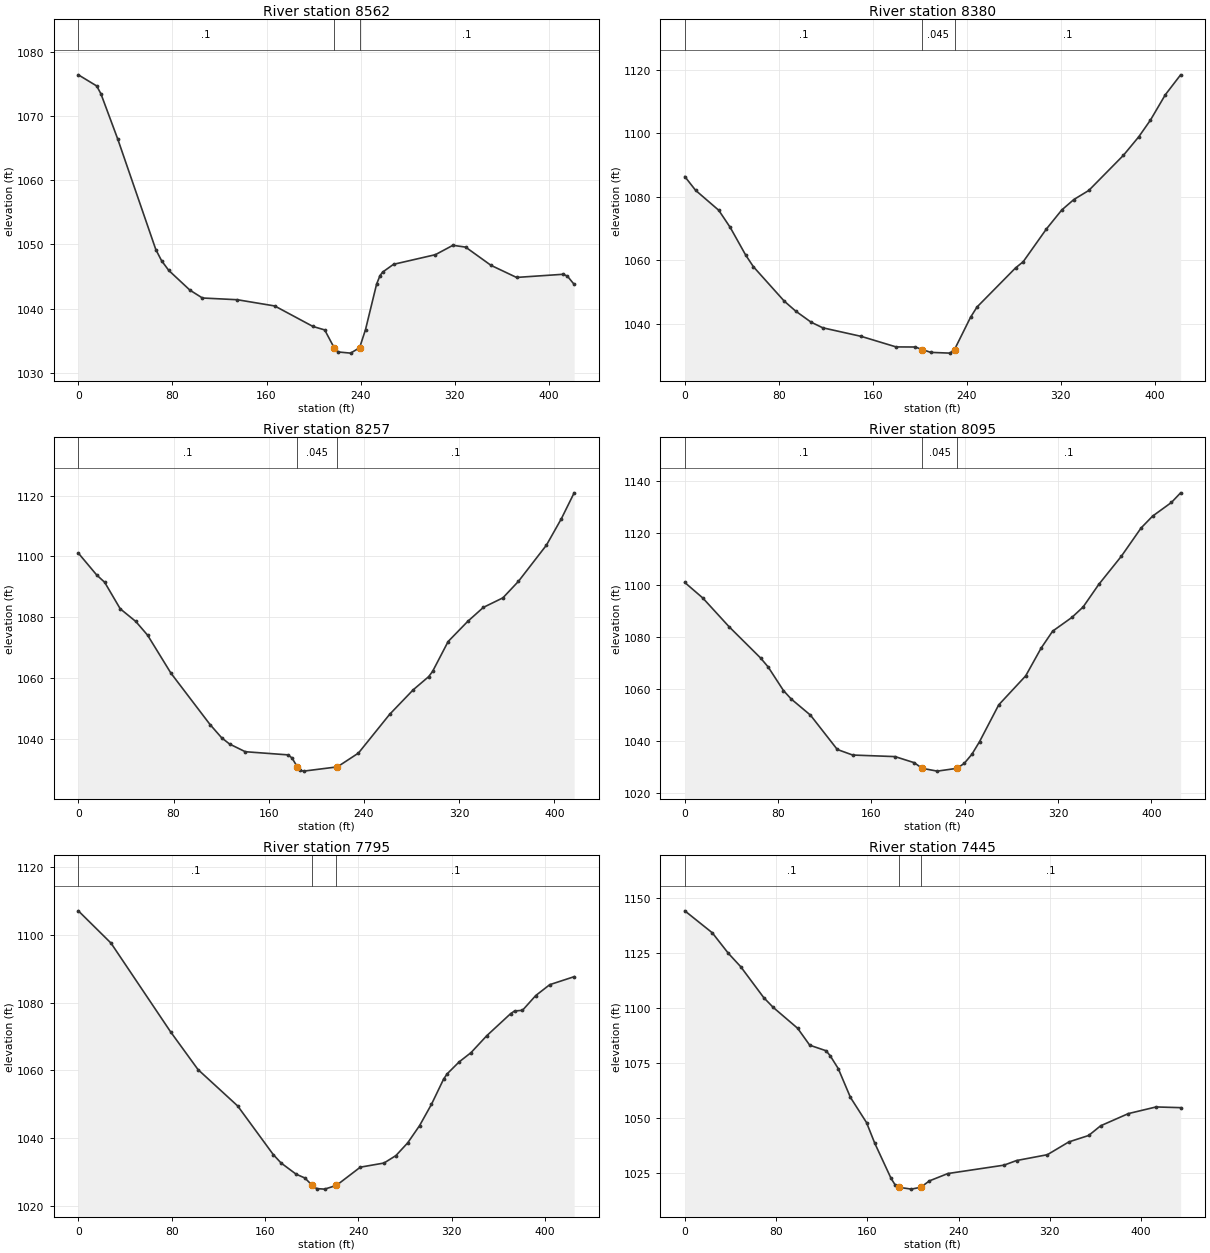
Type RM Length L Ch R = 1 ,8562    ,176.3,181.4,185.8
XS GIS Cut Line= 2
1654954.27853004476682.7499226911654570.68635386476857.744039425
#Sta/Elev= 30
       0 1076.38    15.6 1074.65    19.2 1073.43    33.6 1066.34    65.9 1049.18
    70.8 1047.45    76.9 1045.94    94.9 1042.87   105.5 1041.65   135.2 1041.38
     167 1040.41   199.5 1037.22   209.5 1036.68  217.521033.906   221.1 1033.25
   231.5 1033.07  239.161033.908   244.2 1036.74   253.6  1043.8   256.5 1045.13
   258.8 1045.69     268 1046.89   303.6 1048.39   318.5 1049.85   329.3 1049.57
   350.9 1046.73   372.6 1044.85   412.2 1045.34   415.8 1045.06   421.6 1043.77
#Mann= 3 ,-1,0
       0      .1       0  217.52    .045       0  239.16      .1       0
Bank Sta=217.52,239.16
XS Rating Curve= 0 ,0
Exp/Cntr(USF)=0,0
Exp/Cntr=0.3,0.1

Type RM Length L Ch R = 1 ,8380    ,124.2,123.4,123.7
XS GIS Cut Line= 2
1654923.04763333476595.3613332391654501.05635133476608.208436632
#Sta/Elev= 30
       0 1086.38     9.2 1082.03    28.9 1075.74    38.7 1070.31    51.8 1061.63
    58.4 1057.93    84.7 1047.06    94.5  1043.9   107.6 1040.41   117.5 1038.65
   150.3 1035.94   179.9 1032.62   196.3 1032.59  202.181031.796   209.4  1030.9
   225.8 1030.66  229.68  1031.8   243.3 1041.96   248.8  1045.2   281.6 1057.53
   288.2 1059.52   307.9 1069.83     321 1075.83   331.3 1079.13     344 1081.99
   373.5 1093.08   386.6 1098.94   396.5 1104.19   409.2  1112.2   422.2 1118.47
#Mann= 3 ,-1,0
       0      .1       0  202.18    .045       0  229.68      .1       0
Bank Sta=202.18,229.68
XS Rating Curve= 0 ,0
Exp/Cntr(USF)=0,0
Exp/Cntr=0.3,0.1

Type RM Length L Ch R = 1 ,8257    ,164.1,162.1,161.5
XS GIS Cut Line= 2
1654916.23633075476473.5178265951654499.67424852476483.662413073
#Sta/Elev= 30
       0 1101.08    15.5 1093.86    22.1 1091.51    35.2 1082.78    48.3 1078.61
    58.2 1074.11    77.8 1061.64   110.7 1044.74   120.5 1040.37   127.1 1038.34
   140.3 1035.81   176.3 1034.77   179.6 1033.74  184.021030.832   186.1 1029.67
   189.4 1029.43  217.731030.833   235.4 1035.36   261.6 1048.08   281.4 1056.14
   294.4 1060.47   297.7 1062.19   310.8 1072.03   327.3 1078.66   340.4 1083.24
   356.8 1086.37   369.9 1091.81   393.4  1103.7   405.9 1112.35   416.7 1120.89
#Mann= 3 ,-1,0
       0      .1       0  184.02    .045       0  217.73      .1       0
Bank Sta=184.02,217.73
XS Rating Curve= 0 ,0
Exp/Cntr(USF)=0,0
Exp/Cntr=0.3,0.1

Type RM Length L Ch R = 1 ,8095    ,296.6,300,306.6
XS GIS Cut Line= 6
1654909.50960268476296.9318902491654822.39954068476305.184498429
 1654747.7336795476312.2579750871654648.17974475476321.689058587
1654573.51388359476328.7625352591654486.40382159476337.015143424
#Sta/Elev= 30
       0 1101.01    15.4 1095.05    37.8 1084.04    64.9 1071.94    71.4 1068.49
    84.6 1059.35    91.2 1056.11   107.7 1049.89   130.7 1036.66   143.9 1034.51
   180.2 1033.91   196.6 1031.57  203.491029.389   216.4 1028.31  233.311029.389
   239.5 1031.28   246.1 1034.81   252.7 1039.72   269.1 1053.86   292.2 1065.03
   305.4  1075.7   315.3 1082.26   331.8 1087.55   341.4 1091.56   354.8 1100.25
   374.2 1111.13   391.1 1122.02     401  1126.6   417.1 1131.85     425 1135.57
#Mann= 3 ,-1,0
       0      .1       0  203.49    .045       0  233.31      .1       0
Bank Sta=203.49,233.31
XS Rating Curve= 0 ,0
Exp/Cntr(USF)=0,0
Exp/Cntr=0.3,0.1

Type RM Length L Ch R = 1 ,7795    ,359.4,350,346.8
XS GIS Cut Line= 6
1654950.87139659476077.1908599291654866.19899376476055.127583832
1654793.62236726476036.2158762511654696.85386001476011.000375509
1654624.27723351475992.0889960081654539.60450259475970.025719926
#Sta/Elev= 30
       0 1107.05      28 1097.54    79.1 1071.38   102.6 1060.26   136.6 1049.54
   167.1 1035.21   173.8 1032.73   186.7 1029.43   194.2 1028.31  200.521026.122
   204.4 1025.18   211.1 1025.03  221.19 1026.12   241.7  1031.5     262 1032.72
   272.2 1034.91   282.3 1038.66   292.5 1043.75   302.7 1050.03   313.1 1057.46
   316.2 1059.03   326.4 1062.52   336.6 1065.26   350.1 1070.25   370.5 1076.73
   373.9 1077.53   380.7 1077.73   392.1 1082.09   404.1 1085.29     425 1087.64
#Mann= 3 ,-1,0
       0      .1       0  200.52    .045       0  221.19      .1       0
Bank Sta=200.52,221.19
XS Rating Curve= 0 ,0
Exp/Cntr(USF)=0,0
Exp/Cntr=0.3,0.1

Type RM Length L Ch R = 1 ,7445    ,320.4,324.9,326.6
XS GIS Cut Line= 6
1654949.17648728475607.9691315461654868.56706844475642.003840388
1654799.47304653475671.176682295 1654707.3479027475710.073586138
1654637.44351494475737.3264843841654545.85544354475769.474385963
#Sta/Elev= 30
       0 1144.34    24.1 1134.35    38.3 1124.95      49 1118.95    69.2 1104.88
    77.5 1100.44    98.9 1090.95   109.5 1083.26   123.8 1080.73   127.4 1078.49
   134.5 1072.62   145.2 1059.51   159.3 1048.07   166.5  1038.7   180.8  1022.7
   184.3  1019.8  187.391018.678   198.6 1017.82  206.861018.678   214.4 1021.57
   230.6 1024.91   279.8 1028.72   290.8 1030.82   317.8 1033.47   336.6 1039.28
     354 1042.21   364.5 1046.62   388.8 1052.16   413.1 1055.18   434.6 1054.86
#Mann= 3 ,-1,0
       0      .1       0  187.39    .045       0  206.86      .1       0
Bank Sta=187.39,206.86
XS Rating Curve= 0 ,0
Exp/Cntr(USF)=0,0
Exp/Cntr=0.3,0.1

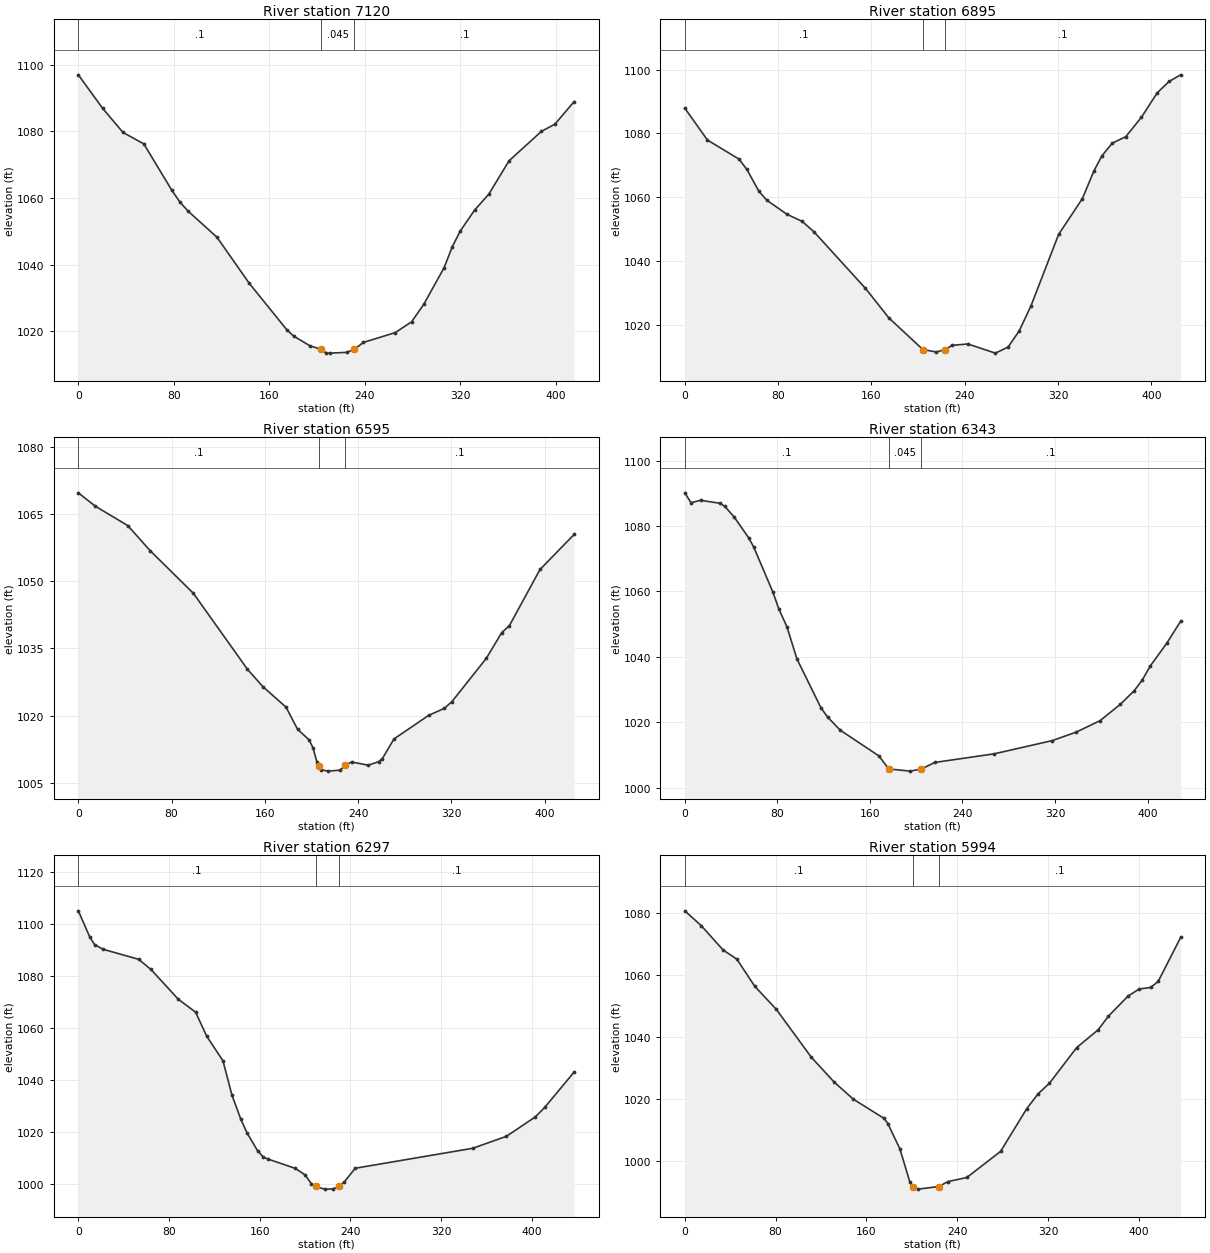
Type RM Length L Ch R = 1 ,7120    ,219.7,225.1,232
XS GIS Cut Line= 2
1654808.85068326475369.3031680881654408.66770267475480.670221834
#Sta/Elev= 30
       0 1096.96    20.4 1086.88    37.4 1079.67    54.9 1076.21    78.3 1062.31
    85.1 1058.75    91.9 1056.06   116.2 1048.17     143 1034.45   174.8 1020.34
   180.5 1018.49   194.1 1015.58  203.421014.538   207.7 1013.44   211.1 1013.39
   224.7 1013.62  231.361014.538   238.7 1016.59   265.6 1019.56   279.2  1022.8
   289.4 1028.04   306.5 1039.08   313.3 1045.35   320.1 1050.12     332 1056.35
   343.9 1061.13   360.9 1071.17   387.9 1079.96   399.3 1082.16   415.4 1088.93
#Mann= 3 ,-1,0
       0      .1       0  203.42    .045       0  231.36      .1       0
Bank Sta=203.42,231.36
XS Rating Curve= 0 ,0
Exp/Cntr(USF)=0,0
Exp/Cntr=0.3,0.1

Type RM Length L Ch R = 1 ,6895    ,300.7,300,298.2
XS GIS Cut Line= 6
1654811.31294867475258.8384940031654726.42532317475237.616423592
1654653.66464192475219.4264993371654556.65040025475195.172938928
1654483.88971901475176.9830146731654399.00209351 475155.76160042
#Sta/Elev= 30
       0 1087.91    19.4  1077.9    46.5 1071.92    53.2 1068.69    63.4 1061.92
    70.1 1059.09    87.5 1054.64   100.6  1052.4   110.7 1049.14   154.7 1031.47
     175  1022.1   204.1 1012.21   215.6 1011.45  223.221012.194   229.1 1013.53
   242.6 1013.96   266.2 1011.09   277.1 1012.97   286.6 1018.04   296.7 1025.88
   320.4  1048.3   340.7 1059.49   350.8  1068.3   357.6 1072.99   366.4 1076.92
   377.9 1078.93   391.4 1085.03   404.9 1092.69   415.1 1096.26     425 1098.35
#Mann= 3 ,-1,0
       0      .1       0   204.1    .045       0  223.22      .1       0
Bank Sta=204.1,223.22
XS Rating Curve= 0 ,0
Exp/Cntr(USF)=0,0
Exp/Cntr=0.3,0.1

Type RM Length L Ch R = 1 ,6595    ,258.9,252,237.2
XS GIS Cut Line= 6
  1654880.566091474942.0904398411654793.80084459474930.773533344
 1654719.4309146474921.0724372571654620.27100793474908.138079926
1654545.90107793474898.4376400111654458.10236901474893.363503173
#Sta/Elev= 30
       0 1069.74    14.6 1066.75    42.5 1062.41    61.5 1056.85    98.8 1047.27
   145.1 1030.33   158.3 1026.46   178.2 1021.87   188.1 1016.93     198 1014.56
   201.3 1012.81   204.6 1009.71   206.21008.837   207.9  1007.9   214.6 1007.58
   224.5  1007.8  229.031008.839   234.4 1009.63   248.8  1008.9   257.6 1009.69
   260.9  1010.4   270.8 1014.76   300.6 1020.04   313.8 1021.58   320.4 1023.06
   350.1  1032.8   363.3 1038.53   369.8 1040.06   396.1 1052.62   425.4 1060.45
#Mann= 3 ,-1,0
       0      .1       0   206.2    .045       0  229.03      .1       0
Bank Sta=206.2,229.03
XS Rating Curve= 0 ,0
Exp/Cntr(USF)=0,0
Exp/Cntr=0.3,0.1

Type RM Length L Ch R = 1 ,6343    ,46.7,46,47.6
XS GIS Cut Line= 3
1654786.89285316474559.3611656471654496.50406525474785.712251424
1654440.07480297474807.269497688
#Sta/Elev= 30
       0 1090.13     5.4 1087.11    13.6 1087.84    30.3 1086.95    34.6 1085.99
    42.8 1082.69    55.3 1076.33    59.5 1073.62    76.1 1059.84    81.3 1054.63
    88.4 1049.08    96.9 1039.41   117.7 1024.43   123.4 1021.62   134.3 1017.62
   167.8 1009.74  176.36 1005.75   194.8 1005.09  204.551005.751   216.1 1007.74
   267.5 1010.38   317.4  1014.4   338.2 1016.98     359 1020.52   376.6 1025.54
   388.5 1029.67   395.5 1032.96   402.5 1037.29   416.6 1044.16   428.6 1050.88
#Mann= 3 ,-1,0
       0      .1       0  176.36    .045       0  204.55      .1       0
Bank Sta=176.36,204.55
XS Rating Curve= 0 ,0
Exp/Cntr(USF)=0,0
Exp/Cntr=0.3,0.1

Type RM Length L Ch R = 1 ,6297    ,308.2,302.6,289.4
XS GIS Cut Line= 6
1654784.20047009474519.1480442581654714.06806442474572.039014593
1654651.50126043474613.567802921 1654566.6890941474666.702867255
1654506.57143217474714.9166815881654431.19592676474776.499235585
#Sta/Elev= 30
       0 1105.03    10.2 1094.89    14.3 1092.07    21.6 1090.28    53.2 1086.39
    64.1 1082.48    88.2 1071.03   103.5 1066.05   113.2 1056.86   127.6 1047.36
   135.5 1034.19   143.4 1024.84   148.8 1019.67   158.2 1012.74     163 1010.45
   166.9 1009.65   191.5 1005.99   199.9 1003.53   205.6 1000.11  209.61 999.053
   217.2  998.03   224.6  998.09  229.77 999.051   234.4  1000.7   244.3 1006.06
   347.9 1013.73   377.6 1018.33     403 1025.76   411.5 1029.48   437.4 1043.06
#Mann= 3 ,-1,0
       0      .1       0  209.61    .045       0  229.77      .1       0
Bank Sta=209.61,229.77
XS Rating Curve= 0 ,0
Exp/Cntr(USF)=0,0
Exp/Cntr=0.3,0.1

Type RM Length L Ch R = 1 ,5994    ,276.9,297.2,309
XS GIS Cut Line= 6
1654417.32784426474329.7675175071654361.18917701474410.997013837
1654342.23022543474484.2107781771654329.82637884474583.438598096
1654320.52324784474657.859381005 1654309.6699231474744.683682427
#Sta/Elev= 30
       0 1080.71    14.5 1075.93    33.8 1068.07    45.8 1065.16    61.7 1056.37
    80.5 1049.02   111.4 1033.56   131.6 1025.53   148.6 1019.98   175.7 1013.79
     179 1012.09   189.6 1003.92   198.4  993.21  200.78991.8418   205.5  991.02
  223.59991.8395   231.9  993.45   248.5  994.77   278.2 1003.16   301.4    1017
   311.3 1021.74   321.2  1025.1   345.3 1036.63   364.2 1042.35   373.3 1046.77
   390.6 1053.24   400.5 1055.53   410.5 1056.01   417.1 1057.94   436.9 1072.13
#Mann= 3 ,-1,0
       0      .1       0  200.78    .045       0  223.59      .1       0
Bank Sta=200.78,223.59
XS Rating Curve= 0 ,0
Exp/Cntr(USF)=0,0
Exp/Cntr=0.3,0.1

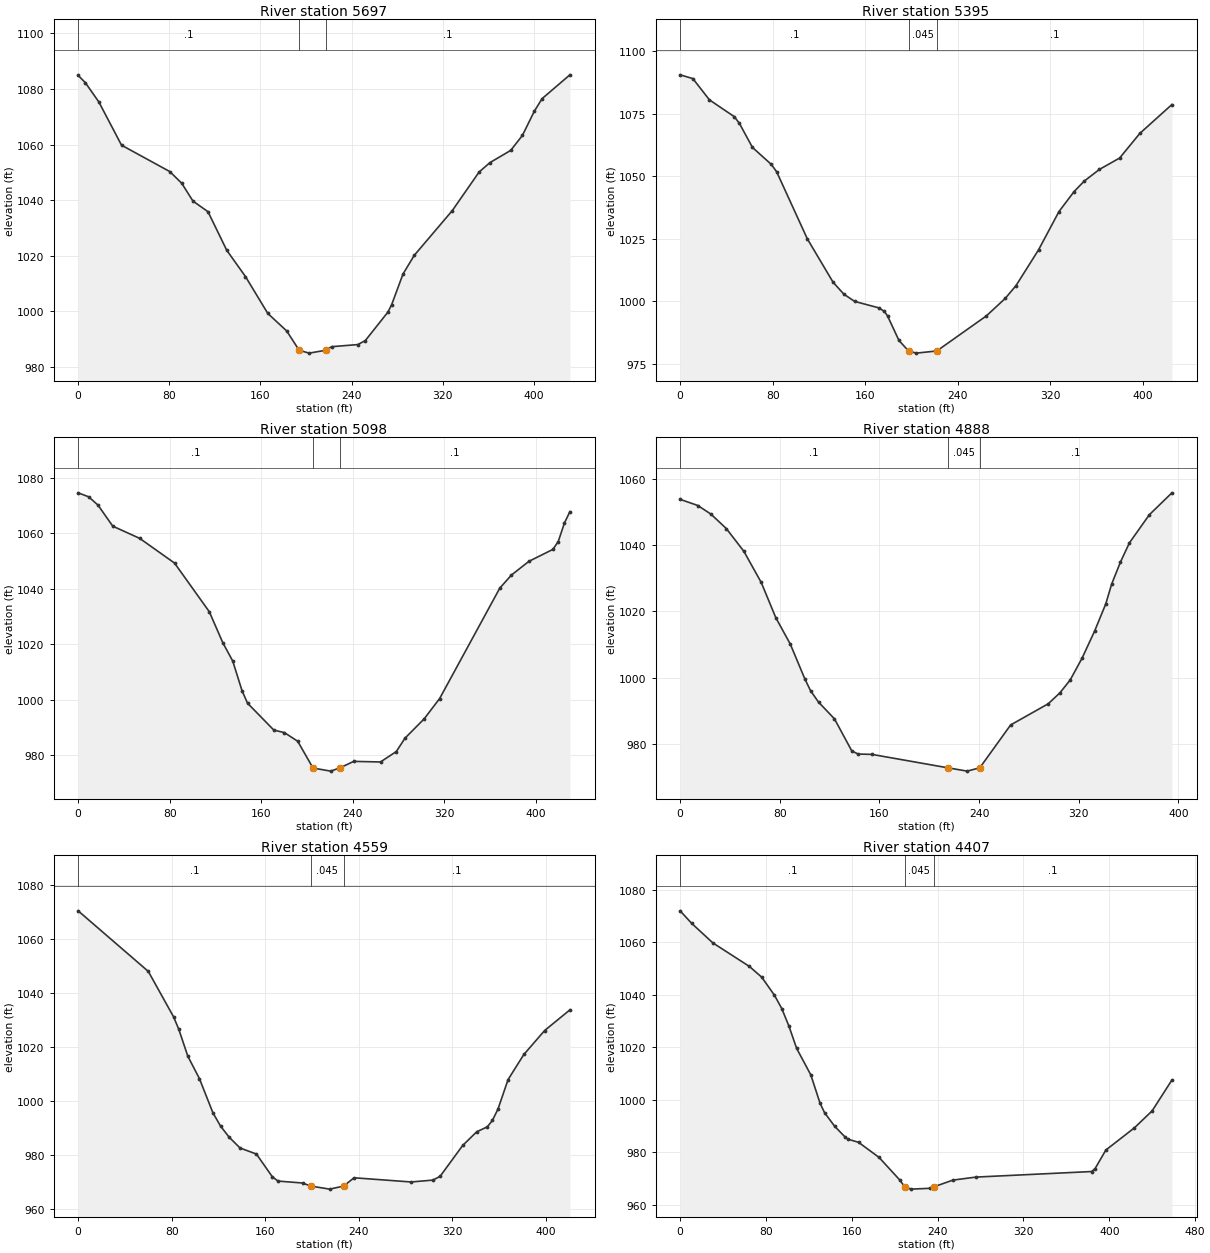
Type RM Length L Ch R = 1 ,5697    ,310.3,302.3,295.3
XS GIS Cut Line= 6
1654388.27639318474282.0514055941654303.08594675474315.565118089
1654228.25210692 474320.553953261654128.47343509474327.205514759
1654054.10809825474339.219270259 1653968.7785445474367.330434501
#Sta/Elev= 30
       0  1084.9     6.3 1082.29    18.2 1075.32    38.1 1059.76    80.4 1050.27
    90.9 1046.07   100.8 1039.63     114  1035.8   130.4 1021.95   146.9 1012.44
   166.5  999.16   183.1  992.84  194.03985.8828   202.8  984.86  217.25 985.885
   222.5  987.18   245.5  987.94   252.1  989.38   271.9  999.62   275.2 1002.29
   285.2 1013.37   295.1  1020.1   328.4 1036.17     352  1050.1   361.5 1053.48
   379.7 1057.87     390 1063.27   400.4 1071.94   407.3 1076.53   431.7  1085.1
#Mann= 3 ,-1,0
       0      .1       0  194.03    .045       0  217.25      .1       0
Bank Sta=194.03,217.25
XS Rating Curve= 0 ,0
Exp/Cntr(USF)=0,0
Exp/Cntr=0.3,0.1

Type RM Length L Ch R = 1 ,5395    ,295.8,296.8,296.5
XS GIS Cut Line= 6
1654161.50289659473953.3571810871654095.99285701474011.362970591
1654039.84172259474061.0823593441653964.97310592474127.374877676
1653908.82164343 474177.094266431653843.31160384474235.100384012
#Sta/Elev= 30
       0 1090.45      11 1088.94    25.3 1080.46    46.8 1073.75    51.2 1071.08
    62.5 1061.47    78.8 1054.69    83.4 1051.75   109.9    1025   132.2 1007.65
   141.5 1002.91   150.8 1000.02   171.7  997.45   176.4  996.06   179.2  994.27
   189.1  984.43   197.4980.2412     204  979.38   221.8980.2408   264.7  994.26
     281 1001.25   290.3 1006.36   309.7 1020.57   327.4  1035.9   340.4 1043.82
   349.1    1048   362.3 1052.69   379.8 1057.24   397.3 1067.09     425  1078.6
#Mann= 3 ,-1,0
       0      .1       0   197.4    .045       0   221.8      .1       0
Bank Sta=197.4,221.8
XS Rating Curve= 0 ,0
Exp/Cntr(USF)=0,0
Exp/Cntr=0.3,0.1

Type RM Length L Ch R = 1 ,5098    ,207.4,209.6,207.6
XS GIS Cut Line= 6
1653992.80900826473732.1138571651653922.19333585473783.782717094
  1653861.666554473828.0716705021653784.80417493473892.268064424
1653728.61399859473945.2157931771653662.53899951474006.536208585
#Sta/Elev= 30
       0 1074.49     9.2 1073.06    17.3  1070.1    30.3 1062.49    53.9 1058.08
    84.3  1049.2   114.7 1031.68   126.5 1020.53   135.2 1013.91   143.3 1003.27
   148.1  998.77   171.1  989.08   180.4  988.16     192  985.05  205.36975.4191
   220.8   974.3  228.59 975.421     241  977.81   264.4   977.6   278.2  981.35
   285.8  986.16   302.6  993.14   316.1 1000.44   368.7 1040.19   378.9  1044.9
   394.2 1049.84   415.1 1054.12   419.8 1056.95   425.2 1063.62     430 1067.73
#Mann= 3 ,-1,0
       0      .1       0  205.36    .045       0  228.59      .1       0
Bank Sta=205.36,228.59
XS Rating Curve= 0 ,0
Exp/Cntr(USF)=0,0
Exp/Cntr=0.3,0.1

Type RM Length L Ch R = 1 ,4888    ,328.9,329.7,327.5
XS GIS Cut Line= 4
1653841.72398888473581.0592400091653791.11580266473621.448311757
1653632.44456825473755.5667650061653543.67423916473839.697743266
#Sta/Elev= 30
       0  1053.8    14.2 1051.94    24.7 1049.34    37.1 1044.97    51.2 1038.08
    65.1  1028.7    76.8 1018.06    88.4 1010.11     100  999.67   104.7     996
   111.1  992.57   123.9  987.51   137.8  977.83   142.9  976.89     154  976.78
  214.84972.7367   230.4  971.73  240.56972.7366   265.3  985.67   295.5  992.07
   304.8  995.34   313.1  999.24   322.6  1005.8   332.7 1013.99   341.7 1022.25
   346.4  1028.2   353.5 1034.89   360.7 1040.68   376.7 1049.17   394.8 1055.77
#Mann= 3 ,-1,0
       0      .1       0  214.84    .045       0  240.56      .1       0
Bank Sta=214.84,240.56
XS Rating Curve= 0 ,0
Exp/Cntr(USF)=0,0
Exp/Cntr=0.3,0.1

Type RM Length L Ch R = 1 ,4559    ,149.9,151.7,146
XS GIS Cut Line= 2
1653616.05987678473333.1810430241653330.26521168473641.822665226
#Sta/Elev= 30
       0  1070.5      60 1048.08    81.6 1031.27    86.1 1026.63    93.8 1016.69
   103.7 1008.41   115.3   995.7   121.8   990.8   129.2  986.67   138.5  982.69
   152.5  980.44   166.2  971.97     171  970.44   191.9  969.73   198.9   968.6
   215.1  967.46  227.01968.5781     236  971.66   284.8  970.11   303.4   970.8
   309.6  972.21   328.9  983.63   340.9   988.7   349.9   990.5   354.3  992.89
   359.1  997.12   367.7 1008.01   381.2 1017.31     399 1026.19   420.6 1033.83
#Mann= 3 ,-1,0
       0      .1       0   198.9    .045       0  227.01      .1       0
Bank Sta=198.9,227.01
XS Rating Curve= 0 ,0
Exp/Cntr(USF)=0,0
Exp/Cntr=0.3,0.1

Type RM Length L Ch R = 1 ,4407    ,84.3,86.3,85.4
XS GIS Cut Line= 4
1653558.98542627473273.9310589251653400.86764322473347.510621338
1653328.07084211 473458.662726261653306.15352564473608.170134993
#Sta/Elev= 30
       0 1071.89    10.7 1067.14    30.4  1059.7    64.6  1050.7    76.1 1046.59
    87.9 1039.75    94.7 1034.69   101.4 1027.99   108.6 1019.49   121.8 1009.41
   130.4  998.63   134.6  995.03     144  989.86   153.9  985.69   156.4  984.92
   166.3  983.74   185.4  977.99   204.5  969.48   209.3  966.81   215.3  965.91
   232.7  966.22   236.7  966.82   254.3  969.35   275.9   970.5   383.5  972.61
   386.8  973.75   396.8  980.79   423.3  989.21   439.9  995.68   458.4 1007.47
#Mann= 3 ,-1,0
       0      .1       0   209.3    .045       0   236.7      .1       0
Bank Sta=209.3,236.7
XS Rating Curve= 0 ,0
Exp/Cntr(USF)=0,0
Exp/Cntr=0.3,0.1