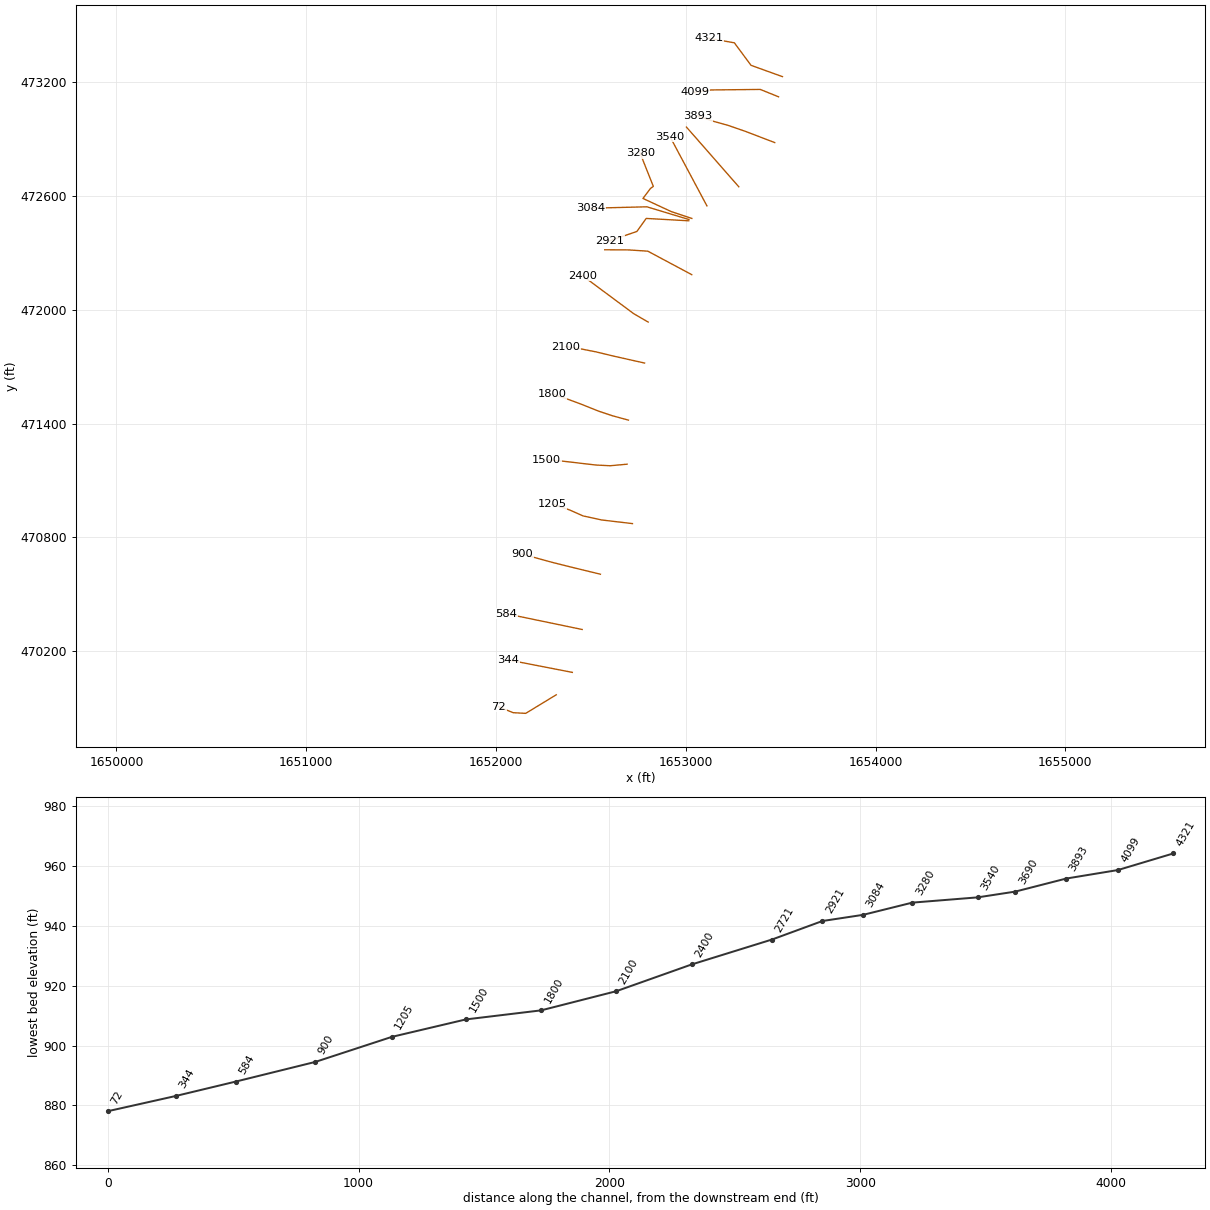
HEC-RAS study LftFkMagtyRn.prj: LftFkMagtyRn

--- LftFkMagtyRn.g01 (geometry) --- (continued)

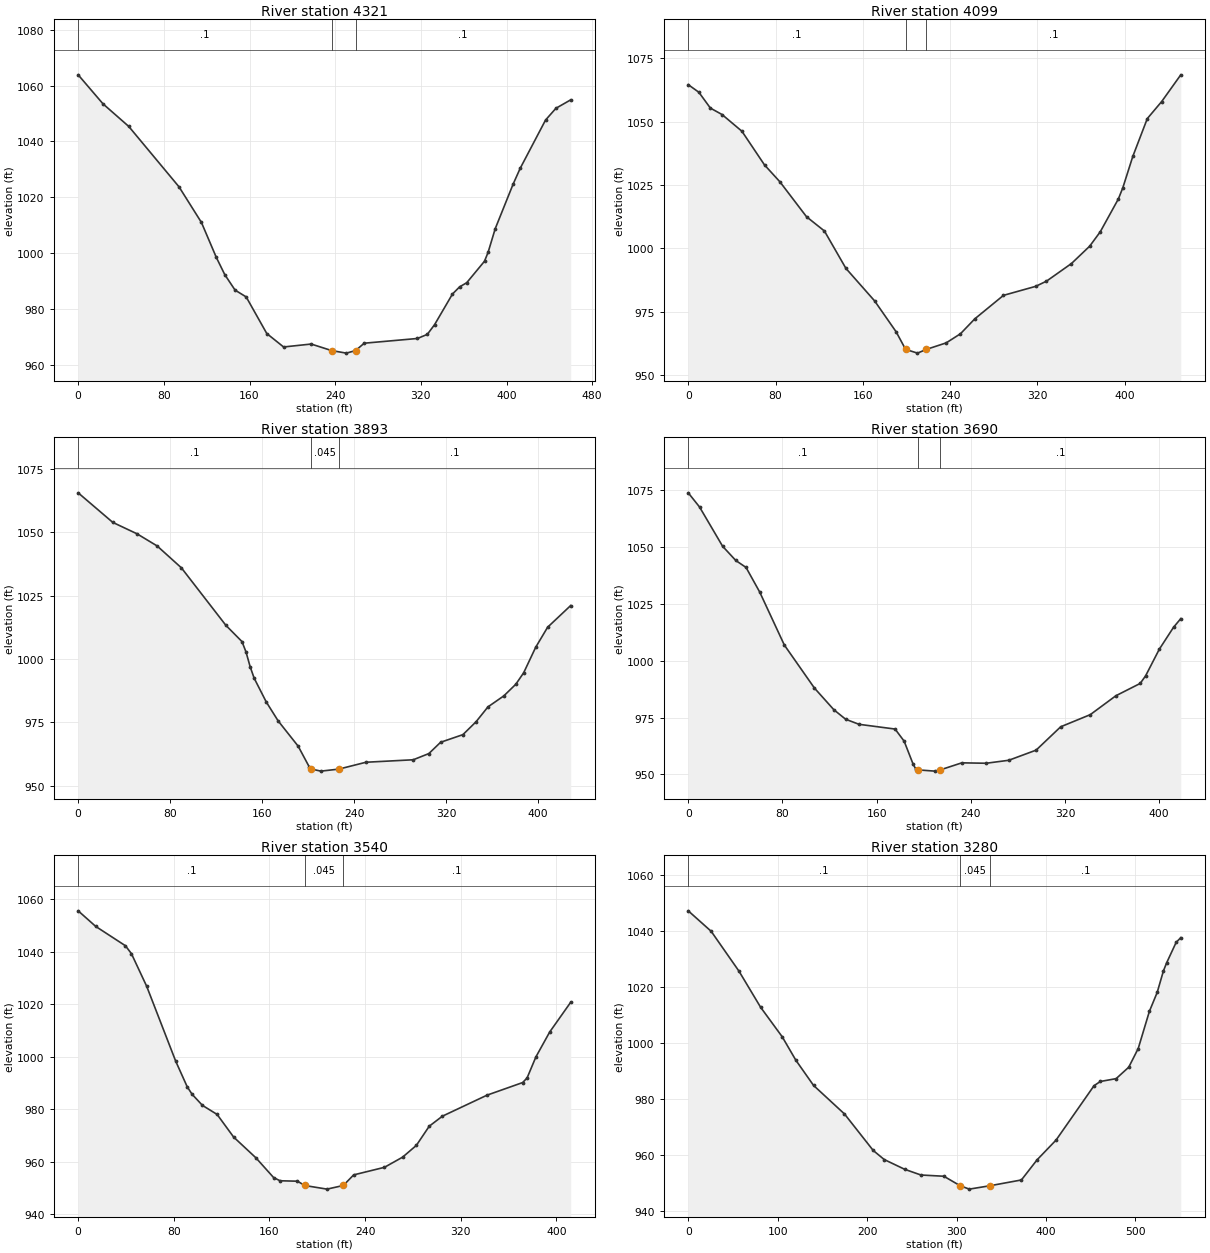
Type RM Length L Ch R = 1 ,4321    ,200.8,221.2,224
XS GIS Cut Line= 4
1653509.69441503473227.6928595791653344.01118128473287.356598935
1653256.29020743473405.9348022081653122.07187714473429.557228339
#Sta/Elev= 30
       0 1063.82    23.2 1053.43    47.2 1045.37    94.2 1023.73   115.1    1011
     129  998.49   136.9  992.33   146.5   986.8   156.9  984.35   176.1  971.27
   191.8  966.45   217.6   967.5  236.69965.1588   250.4  964.25  258.97965.1538
   267.1   967.8   316.8  969.49     326  970.96   332.8  974.44   349.5   985.4
   356.1  987.94   362.8  989.44   379.4  997.13   382.8 1000.36   389.4 1008.76
   406.1 1024.69   412.7 1030.35   436.4 1047.64   446.1 1051.85   459.9 1054.87
#Mann= 3 ,-1,0
       0      .1       0  236.69    .045       0  258.97      .1       0
Bank Sta=236.69,258.97
XS Rating Curve= 0 ,0
Exp/Cntr(USF)=0,0
Exp/Cntr=0.3,0.1

Type RM Length L Ch R = 1 ,4099    ,209.4,206.3,201.9
XS GIS Cut Line= 4
1653489.18887277473121.4677464671653392.71596861 473160.34496531
1653132.80605536473157.5772543111653046.16810528473145.338433639
#Sta/Elev= 30
       0 1064.55     9.7 1061.57    20.3 1055.31      31 1052.77    49.2 1046.18
    69.9  1032.9      84 1026.25   108.4 1012.47   124.8 1006.85   144.5  992.11
   170.8  979.29   190.5  967.11   199.2960.1733   210.1  958.69  218.32960.1732
   236.4  962.73   249.5  966.33   262.6   972.2   288.9  981.47   318.4  985.02
   328.3  987.06   351.2  994.02   367.9 1000.86   377.6 1006.53   394.2 1019.49
   398.3 1023.92   407.4 1036.23   420.7 1051.17   433.9  1057.9   451.4 1068.43
#Mann= 3 ,-1,0
       0      .1       0   199.2    .045       0  218.32      .1       0
Bank Sta=199.2,218.32
XS Rating Curve= 0 ,0
Exp/Cntr(USF)=0,0
Exp/Cntr=0.3,0.1

Type RM Length L Ch R = 1 ,3893    ,207.3,202.9,195.8
XS GIS Cut Line= 6
1653468.87895375472880.2353115831653387.18685992472911.582689837
1653317.16501833472938.4517305941653222.60516809472971.155733421
1653149.74245292 472991.405692921653064.11696801473020.301960588
#Sta/Elev= 30
       0 1065.45    30.1 1053.81    51.2 1049.31    68.7 1044.53    89.8 1035.91
   128.5 1013.27   142.5 1006.87     146  1002.8   149.6  996.99   153.1  992.45
   163.6  983.11     174  975.61   191.4  965.66   200.9  957.62  202.91956.6405
   211.2  955.84  226.83956.6391   250.4  959.34   291.5  960.31   305.1  962.76
   315.3   967.2   334.7  970.21   346.1  975.26   356.5  981.14   370.3  985.47
   380.7  990.04   387.6   994.6     398 1004.59   408.4 1012.51   428.5 1021.07
#Mann= 3 ,-1,0
       0      .1       0  202.91    .045       0  226.83      .1       0
Bank Sta=202.91,226.83
XS Rating Curve= 0 ,0
Exp/Cntr(USF)=0,0
Exp/Cntr=0.3,0.1

Type RM Length L Ch R = 1 ,3690    ,151.6,150,147
XS GIS Cut Line= 2
 1653279.5917632472647.4760592551653003.68551992472962.009176594
#Sta/Elev= 30
       0 1073.71     9.6 1067.49    29.2 1050.24    40.4 1043.99    49.1 1040.94
    60.7 1030.14    81.6 1006.88   107.2  987.96   123.7  978.44   133.7  974.27
   145.1  972.04   175.7  969.96   183.4  964.64   190.9  954.71   193.2  952.45
  194.81  952.04   209.5  951.48   214.2  952.05   232.4  955.12   253.1  954.94
   272.3  956.25   295.5   960.7   316.4  970.96   341.5  976.28   363.3   984.6
   383.9  989.99   388.5  993.32   400.1 1004.98   412.3  1014.7   418.4 1018.46
#Mann= 3 ,-1,0
       0      .1       0  194.81    .045       0   214.2      .1       0
Bank Sta=194.81,214.2
XS Rating Curve= 0 ,0
Exp/Cntr(USF)=0,0
Exp/Cntr=0.3,0.1

Type RM Length L Ch R = 1 ,3540    ,269.3,260.5,231
XS GIS Cut Line= 2
1653111.63312992472546.7405891851652917.75800486472910.204318099
#Sta/Elev= 30
       0 1055.68    14.7 1049.73    39.5 1042.37    44.5 1039.38    57.3  1026.9
    81.5  998.42    91.2  988.56    95.3  985.71   103.9   981.5   116.2  978.03
     130  969.41   148.6  961.51   163.4  953.98   168.8  952.74   183.4  952.57
  189.45950.9346   208.1  949.55   221.7950.9365   230.4  954.98   256.1  957.86
   271.3  961.74   282.8  966.22   293.6  973.55   304.6  977.37   341.9  985.38
   371.7  990.19   375.4  991.93   382.8  999.98   394.3 1009.45   411.9 1020.82
#Mann= 3 ,-1,0
       0      .1       0  189.45    .045       0   221.7      .1       0
Bank Sta=189.45,221.7
XS Rating Curve= 0 ,0
Exp/Cntr(USF)=0,0
Exp/Cntr=0.3,0.1

Type RM Length L Ch R = 1 ,3280    ,170.7,195.9,229.9
XS GIS Cut Line= 6
1653031.99498501  472480.66491651652924.10871784472516.508348763
1652774.59564074472585.9569749551652813.86490005472638.320743666
1652829.26485287472649.5220646441652760.03970433472823.774818969
#Sta/Elev= 30
       0 1047.36    25.6 1040.05    56.7 1025.79    80.9 1012.87   105.1 1002.28
   120.3  993.92   140.1   984.9   174.7  974.68   206.8  961.63   219.1  958.38
   242.1  954.87   260.2  952.84   285.8   952.4  304.02949.0055   314.2  947.79
  337.45949.0063   372.5  951.07   390.1   958.3   411.3  965.36   453.7  984.79
   460.7   986.3   478.4  987.32   492.5  991.41   503.1  998.09   515.6  1011.4
   524.3 1018.15   531.3 1025.88   534.9 1028.77   545.5 1036.07   550.7 1037.77
#Mann= 3 ,-1,0
       0      .1       0  304.02    .045       0  337.45      .1       0
Bank Sta=304.02,337.45
XS Rating Curve= 0 ,0
Exp/Cntr(USF)=0,0
Exp/Cntr=0.3,0.1

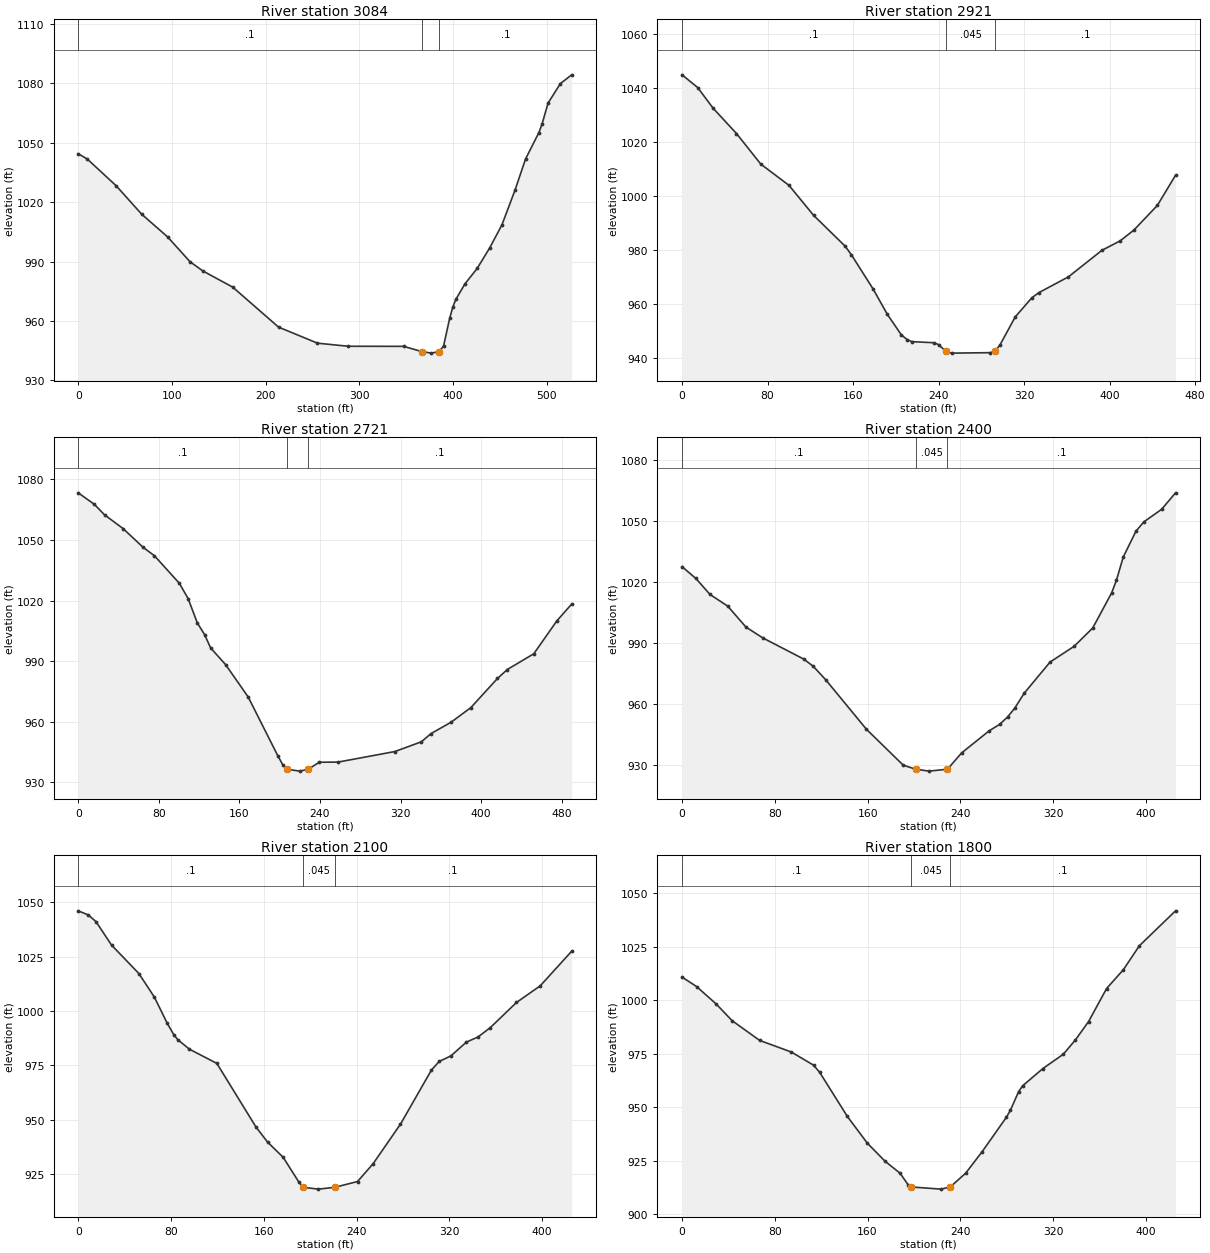
Type RM Length L Ch R = 1 ,3084    ,151.3,162.6,168.8
XS GIS Cut Line= 3
1653016.97386836472474.8527070431652795.27768376 472541.89792416
1652500.30080095472534.481564341
#Sta/Elev= 30
       0 1044.48     9.7  1041.8    40.5  1028.3    67.9 1013.85    95.3 1002.51
   119.3  989.92     133  985.25     165  977.04   213.8  956.86   255.4  948.74
   288.2  947.18   347.3  947.13     367  944.47   376.8  943.71  385.36  944.47
   389.9  947.22   396.5  961.35   399.8  966.95   403.1  970.92   412.9  978.79
   425.8  986.49   439.2   996.9   452.3 1008.58   466.2 1026.05   477.5 1041.87
   491.7 1055.17     495 1059.35   501.5 1070.08   514.7 1079.96   526.7 1084.37
#Mann= 3 ,-1,0
       0      .1       0     367    .045       0  385.36      .1       0
Bank Sta=367,385.36
XS Rating Curve= 0 ,0
Exp/Cntr(USF)=0,0
Exp/Cntr=0.3,0.1

Type RM Length L Ch R = 1 ,2921    ,221,200.5,178.7
XS GIS Cut Line= 4
1653015.71136087472468.1103999471652791.79354347 472480.64523869
1652742.58941813472411.908930863 1652597.9680516472362.422677375
#Sta/Elev= 30
       0 1044.85    14.6 1040.13    29.1 1032.44    50.9 1023.08    73.7 1011.72
     100 1003.87     123  992.77   152.6  981.29   158.4  978.12   178.9  965.32
     192  956.05   205.2  948.39   210.6  946.66     215   945.9     236  945.49
     240  944.77  246.85942.3237   252.1  941.64   288.4  941.81  292.76 942.323
   297.4  944.66   311.7  955.06   327.2  962.14   333.7  964.05   361.5  969.93
   392.7  979.74     410   983.3   422.8   987.3   444.7  996.43   461.7  1007.6
#Mann= 3 ,-1,0
       0      .1       0  246.85    .045       0  292.76      .1       0
Bank Sta=246.85,292.76
XS Rating Curve= 0 ,0
Exp/Cntr(USF)=0,0
Exp/Cntr=0.3,0.1

Type RM Length L Ch R = 1 ,2721    ,321.1,320.8,318.8
XS GIS Cut Line= 6
1653031.79982445 472184.330464861652954.63068745472225.575461109
1652888.48547854472260.9287368551652800.29208537472308.065781687
1652699.59937338472314.7127500221652573.16261838472315.491291766
#Sta/Elev= 30
       0 1073.36    16.1 1067.63    26.1 1062.47    44.7 1055.59    64.5 1046.33
    75.7 1042.17   100.4 1028.53   109.1 1020.98   118.2 1008.94   125.5 1003.07
   131.5  996.47   146.3  988.26   168.7  972.23   198.4  942.83     203  938.69
  207.36936.4017     220  935.46  228.44936.4016   239.3  939.86   257.9  939.93
   314.4  945.17   340.7     950   350.3  954.08   370.2  959.69   389.9  966.98
   416.2  981.36     426  985.81   452.3  993.62   475.2 1009.92   489.9 1018.25
#Mann= 3 ,-1,0
       0      .1       0  207.36    .045       0  228.44      .1       0
Bank Sta=207.36,228.44
XS Rating Curve= 0 ,0
Exp/Cntr(USF)=0,0
Exp/Cntr=0.3,0.1

Type RM Length L Ch R = 1 ,2400    ,296.1,300.3,307.3
XS GIS Cut Line= 6
1652802.21526083471934.4202740941652726.05924517471978.624582008
1652665.82675409472023.3128128351652585.51654726472082.897339344
1652525.28405617472127.5855701711652455.01319934472179.722605005
#Sta/Elev= 30
       0  1027.5    11.9 1021.73    24.1 1013.85    39.3 1008.18    55.1  997.85
    69.6  992.54     105  982.11   113.2  978.57   123.9  971.96     159  947.67
   190.8  930.01  201.54928.0475     213  927.11  228.92928.0481   241.1  936.06
   264.9  946.92   273.9  950.07   280.7  953.69   286.9  958.01   295.1   965.4
   317.4  980.68   338.1  988.38   354.2  997.42   370.5 1014.65   374.6  1020.8
   380.5 1032.23   391.5 1044.98   398.2 1049.48   413.6 1055.69   425.6 1063.78
#Mann= 3 ,-1,0
       0      .1       0  201.54    .045       0  228.92      .1       0
Bank Sta=201.54,228.92
XS Rating Curve= 0 ,0
Exp/Cntr(USF)=0,0
Exp/Cntr=0.3,0.1

Type RM Length L Ch R = 1 ,2100    ,300.2,299.7,296.2
XS GIS Cut Line= 6
1652783.15197876471718.712700263  1652697.759433471737.738252759
 1652624.5551831471754.0466190871652527.33457701471777.465863585
1652453.66740151471791.9861757611652366.88411051471805.532080427
#Sta/Elev= 30
       0 1046.02     8.6 1044.14    15.3 1041.09    28.7 1030.29    52.3 1017.22
    65.7 1006.35    76.7  994.39    82.5  989.01    85.9   986.8    95.9  982.45
   119.5  975.93   153.1  946.83   163.2   939.8   176.7  932.79   190.2  921.41
     194918.9988   207.1  918.17  221.11918.9988   240.8  921.67   254.3   929.9
   277.8  948.01   304.5  972.87   311.2  976.82   321.3  979.38   334.6   985.7
   344.6  988.05   355.2  992.34   377.8 1003.91   398.3 1011.57   425.4 1027.47
#Mann= 3 ,-1,0
       0      .1       0     194    .045       0  221.11      .1       0
Bank Sta=194,221.11
XS Rating Curve= 0 ,0
Exp/Cntr(USF)=0,0
Exp/Cntr=0.3,0.1

Type RM Length L Ch R = 1 ,1800    ,295.5,300,304.4
XS GIS Cut Line= 6
  1652698.239747471417.8100868461652613.42069092471440.979331836
1652542.14819567471464.7410953341652449.30061235471501.880456761
1652378.93100242471527.9004178351652295.68641825471555.390520334
#Sta/Elev= 30
       0 1010.72    12.5 1006.31    29.5  998.13    43.1  990.41    66.9  981.17
    94.2  975.76   113.4  969.63   118.6  966.36   142.6  945.67   159.9  933.15
   175.3  924.69   188.1  919.17   195.2  913.63  197.75 912.763   223.4  911.76
  231.31912.7621   244.6  919.17   258.8  929.18   279.8  945.31   283.3  948.64
   290.3  957.23   293.8  959.99   311.3  968.06   328.8  974.67   339.3  981.38
   350.7  989.98   366.2 1005.37   380.7 1014.17   394.5 1025.35   425.7 1041.65
#Mann= 3 ,-1,0
       0      .1       0  197.75    .045       0  231.31      .1       0
Bank Sta=197.75,231.31
XS Rating Curve= 0 ,0
Exp/Cntr(USF)=0,0
Exp/Cntr=0.3,0.1

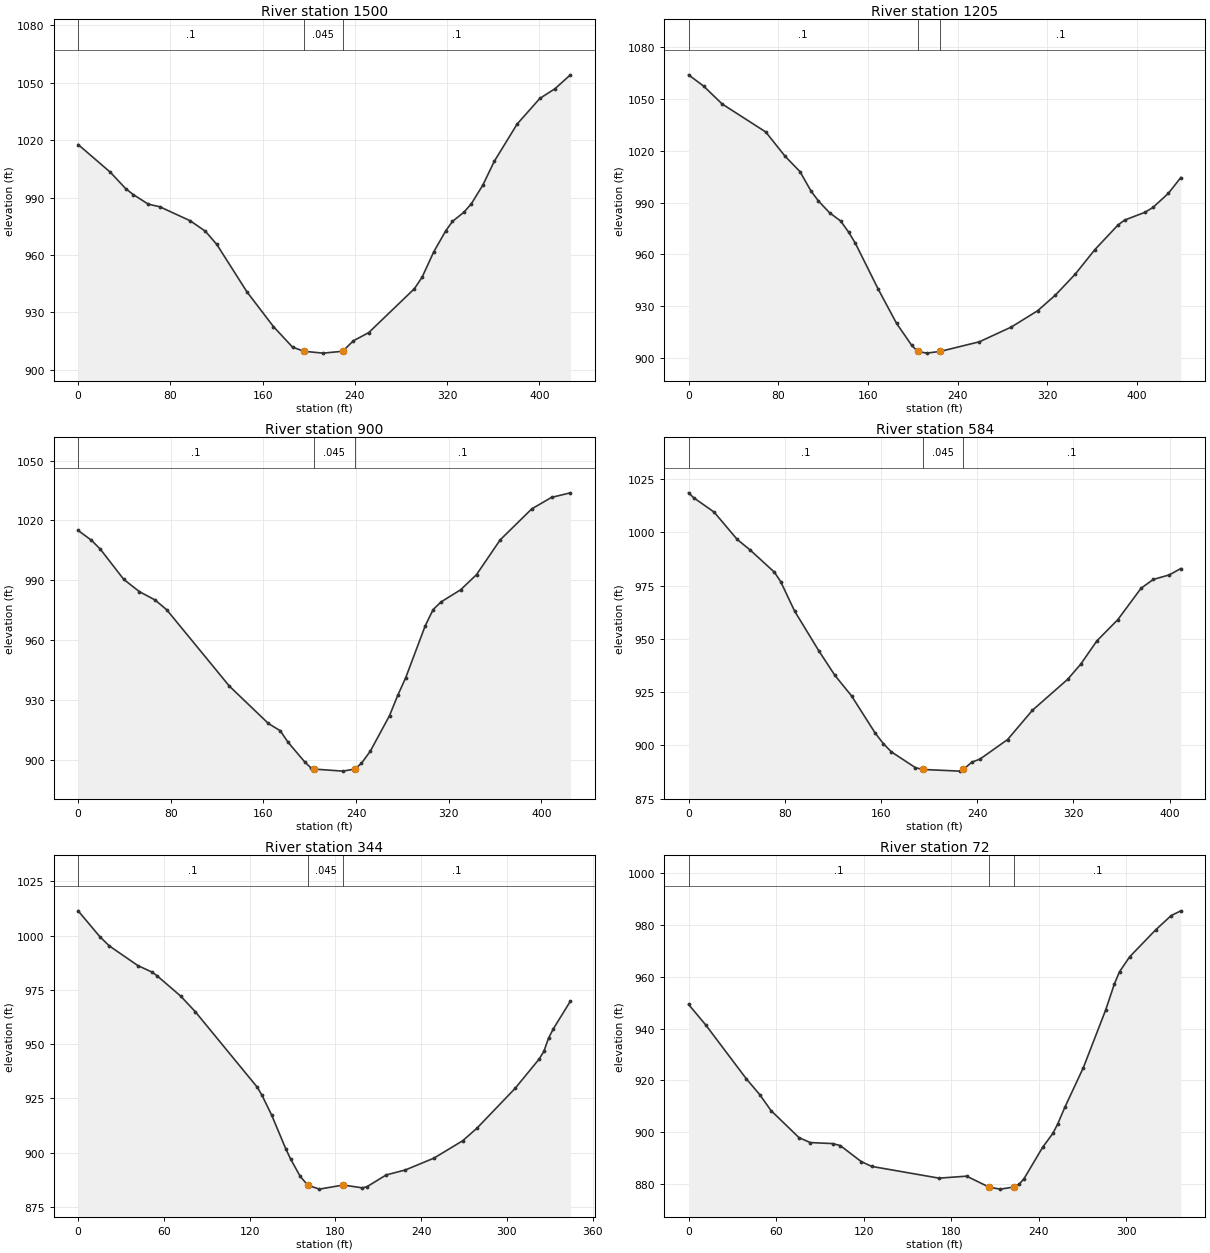
Type RM Length L Ch R = 1 ,1500    ,292.6,295.1,294.2
XS GIS Cut Line= 6
 1652691.1278846471185.6852229981652602.25535892471177.518900752
1652527.17775318471181.2075416741652427.84953976471192.779368922
1652353.35362576471201.4581573461652266.09920709471208.646463171
#Sta/Elev= 30
       0 1017.74      28 1003.22    41.2  994.71    47.8  991.59    60.9  986.56
    70.8  985.23    97.2   977.9   110.3  972.46   120.2  965.58   146.4  940.76
   169.4   922.6     186  911.86  195.83909.6978   212.4  908.73  229.37 909.698
   238.8  915.21     252  919.42   291.7  942.41   298.3  948.36   308.5  961.72
     319  972.79   324.7  977.58   334.6  982.34   341.1  986.82   351.1  996.63
     361 1009.02   380.8 1028.45   400.5 1041.85   413.6  1046.9     427 1054.17
#Mann= 3 ,-1,0
       0      .1       0  195.83    .045       0  229.37      .1       0
Bank Sta=195.83,229.37
XS Rating Curve= 0 ,0
Exp/Cntr(USF)=0,0
Exp/Cntr=0.3,0.1

Type RM Length L Ch R = 1 ,1205    ,303.5,304.5,308.1
XS GIS Cut Line= 6
1652719.28924559470872.6520564261652632.38882884470882.876445428
1652557.90275735470891.6405355041652458.78123643470913.219888672
1652386.47790334470945.2778954211652295.08963467470975.281444341
#Sta/Elev= 30
       0 1064.02    13.5 1057.48      30 1047.13    68.9 1030.93    86.2 1016.83
    99.4 1008.02   109.3  996.69   115.9  990.99   125.8  984.18   135.7  979.39
   142.8  972.99   148.9  966.43   169.2  939.97   185.6  920.11   199.2  907.32
  204.45903.8962   212.5  902.89  224.64 903.897   259.5  909.46   287.9  917.97
   311.4  927.41   327.3  936.48   344.9  948.54   362.5   962.8   383.2   977.1
   389.1  979.93   407.1  984.39   414.3  987.21   428.1   995.4   439.2 1004.56
#Mann= 3 ,-1,0
       0      .1       0  204.45    .045       0  224.64      .1       0
Bank Sta=204.45,224.64
XS Rating Curve= 0 ,0
Exp/Cntr(USF)=0,0
Exp/Cntr=0.3,0.1

Type RM Length L Ch R = 1 ,900     ,314.4,316.4,315.7
XS GIS Cut Line= 6
1652550.60323125470605.9281804261652465.58174776 470626.60661675
 1652392.7068935470644.3332873431652295.70249434470668.636388332
 1652223.3332165 470688.442451091652138.98955317470711.907955334
#Sta/Elev= 30
       0 1014.99    11.4 1010.12    19.1 1005.67    39.4  990.49    52.9  984.37
    66.4  980.21    76.5  975.29   130.6  937.07   164.3  918.37   174.5  914.76
   181.2  909.03   195.9  898.98   201.5   895.9  203.66 895.563   228.6  894.53
  238.76895.5627   244.6  898.41   252.3  904.53   268.9  922.32     276  932.48
   282.8   941.2   299.8  967.39   306.6  975.43   313.4  979.23   330.3   985.3
     344  992.88   364.5 1010.32   391.7 1025.78   408.8 1031.55   425.1 1033.83
#Mann= 3 ,-1,0
       0      .1       0  203.66    .045       0  238.76      .1       0
Bank Sta=203.66,238.76
XS Rating Curve= 0 ,0
Exp/Cntr(USF)=0,0
Exp/Cntr=0.3,0.1

Type RM Length L Ch R = 1 ,584     ,236.9,240.2,238.5
XS GIS Cut Line= 2
1652454.33566739470314.745684735 1652053.5232684470397.847746046
#Sta/Elev= 30
       0 1018.52     4.4 1016.16    21.2 1009.51    40.5  996.63    51.3  991.67
    71.4  981.29    76.6  976.88    88.2  963.04   108.3  944.43   121.7  932.89
   135.5  923.29   155.2  905.83   161.9  900.91   168.6  897.04   188.7  889.58
  194.83888.7545   225.6  887.97  228.49888.7538   235.6   892.2   242.3   893.6
   265.3   902.8   285.9   916.5   315.3  931.08   326.1  938.16   339.5  949.06
   356.9  959.01   376.3  973.79   386.4  977.88   399.8  980.04   409.3  983.01
#Mann= 3 ,-1,0
       0      .1       0  194.83    .045       0  228.49      .1       0
Bank Sta=194.83,228.49
XS Rating Curve= 0 ,0
Exp/Cntr(USF)=0,0
Exp/Cntr=0.3,0.1

Type RM Length L Ch R = 1 ,344     ,270.4,271.5,270.8
XS GIS Cut Line= 2
1652402.44123301470088.7248188291652064.28835043470154.476768219
#Sta/Elev= 30
       0 1011.41    15.1  999.56    21.7  995.29    41.8  986.17    51.8  983.13
    55.2   981.5    71.8  972.08    81.9  964.97   125.4  930.07   128.7  926.32
   135.4  917.29   145.4  901.57   148.7  896.99   155.4  889.01  160.71 884.945
   168.8  883.13   185.5  885.02   198.9  883.72   202.2  884.28   215.6  889.68
     229  891.97     249  897.42   269.1  905.43   279.1  911.23   305.8  929.57
   322.5  942.99   325.9  946.58   329.2  952.74   332.6  957.08   344.5  969.79
#Mann= 3 ,-1,0
       0      .1       0  160.71    .045       0   185.5      .1       0
Bank Sta=160.71,185.5
XS Rating Curve= 0 ,0
Exp/Cntr(USF)=0,0
Exp/Cntr=0.3,0.1

Type RM Length L Ch R = 1 ,72      ,,,
XS GIS Cut Line= 4
 1652317.7937314469970.7206259491652156.82936608469872.699215665
1652090.41566673469876.3958205471652014.09762364 469907.43010281
#Sta/Elev= 30
       0  949.38    11.8  941.44    39.6  920.64    48.8  914.54    56.5  908.39
    75.7  897.93    83.4  896.02    98.7  895.62     104  894.86   118.3   888.7
   125.5  886.81   171.7  882.27   190.6  883.04   206.1  878.77   213.6  878.03
   223.4  878.85   226.7  879.97     230  882.13   242.8  894.27   249.7  899.55
     253  903.16     258  909.75   270.6  924.95   285.9  947.22   291.8  957.16
   295.4  962.01   302.4   967.8   320.1  978.13   330.8  983.69   337.4  985.52
#Mann= 3 ,-1,0
       0      .1       0   206.1    .045       0   223.4      .1       0
Bank Sta=206.1,223.4
XS Rating Curve= 0 ,0
Exp/Cntr(USF)=0,0
Exp/Cntr=0.3,0.1
LCMann Table=0

Chan Stop Cuts=-1
Use User Specified Reach Order=0
Composite Channel Slope=5